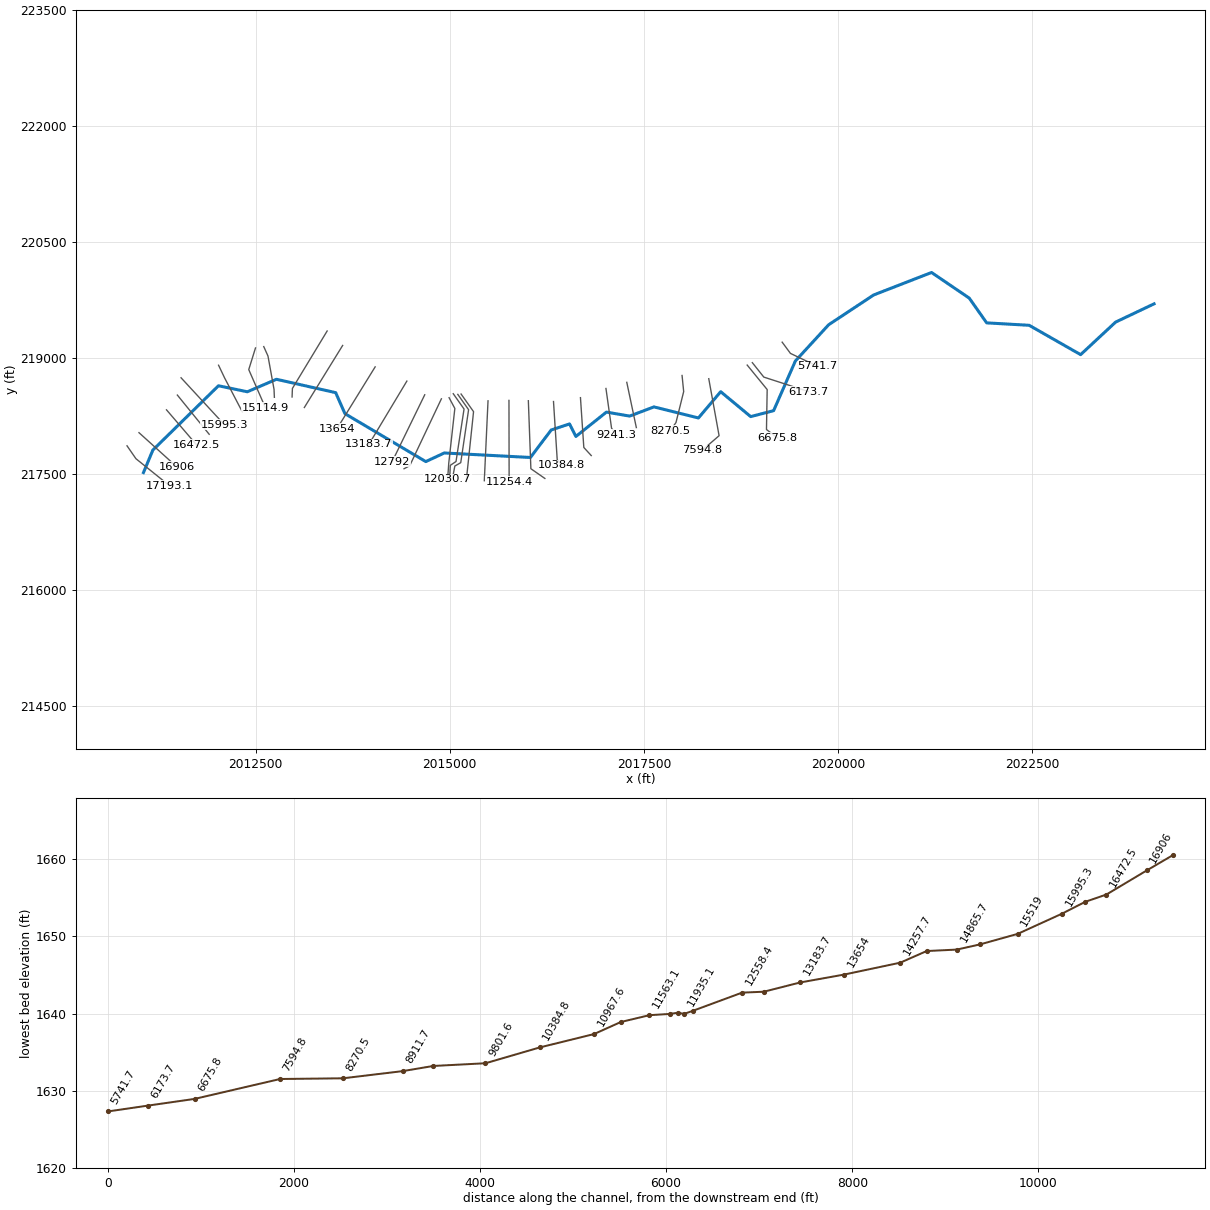
--- WOLFCK.prj (project) ---

Proj Title=WOLFCK
Current Plan=p01
Default Exp/Contr=0,0
English Units
Geom File=g01
Flow File=f01
Plan File=p01
BEGIN DESCRIPTION:
END DESCRIPTION:
DSS Export Rating Curves= 0
DSS Export Rating Curve Sorted= 0
DSS Export Volume Flow Curves= 0
DXF OffsetX= 0
DXF OffsetY= 0
DXF ScaleX= 0
DXF ScaleY= 0

--- WOLFCK.p01 (plan) ---

Plan Title=Floodplain
Program Version=4.00
Geom File=g01
Flow File=f01
K Sum by GR=0
Std Step Tol=0.01
Critical Tol=0.01
Num of Std Step Trials=20
Max Error Tol=0.3
Flow Tol Ratio=0.001
Split Flow NTrial=30
Split Flow Tol=0.02
Split Flow Ratio=0.02
Log Output Level=0
Friction Slope Method=1
Unsteady Friction Slope Method=2
Unsteady Bridges Friction Slope Method=1
Global Log Level=0
CheckData=False
Run HTab=0
Run UNet=0
Run PostProcess=0
UNET Theta=0
UNET Theta Warmup=0
UNET ZTol=0
UNET ZSATol=0
UNET MxIter=0
UNET MaxInSteps=0
UNET DtIC=0
UNET DtMin=0
UNET MaxCRTS=0
UNET WFStab=0
UNET SFStab=0
UNET WFX=0
UNET SFX=0
UNET DSS MLevel=0
UNET DZMax Abort=0
UNET Convert EG Bridges=0
UNET Use Existing IB Tables=0
UNET Froude Limit=0
UNET Froude Power=0
Write IC File=0
Echo Input=False
Echo Output=False
Write Detailed=0

--- WOLFCK.f01 (steady flow) ---

Flow Title=NFF Regression Equation
Program Version=4.10
Number of Profiles= 1
Profile Names=P100yr
River Rch & RM=WOLFCK,Main            ,17193.1
521.5776
River Rch & RM=WOLFCK,Main            ,16906
521.7997
River Rch & RM=WOLFCK,Main            ,16472.5
782.9759
River Rch & RM=WOLFCK,Main            ,14865.7
825.8277
River Rch & RM=WOLFCK,Main            ,14541.9
1257.383
River Rch & RM=WOLFCK,Main            ,12558.4
1277.308
River Rch & RM=WOLFCK,Main            ,12030.7
1439.458
River Rch & RM=WOLFCK,Main            ,9241.3
1511.503
River Rch & RM=WOLFCK,Main            ,6675.8
1677.085
River Rch & RM=WOLFCK,Main            ,4891
1780.299
River Rch & RM=WOLFCK,Main            ,3592.2
1889.071
River Rch & RM=WOLFCK,Main            ,434.5
2066.392
River Rch & RM=WOLFCK,Main            ,61
2068.491
Boundary for River Rch & Prof#=WOLFCK,Main            , 1
Up Type= 0
Dn Type= 1
Dn Known WS=1441.4
DSS Import GetInterval= 0
DSS Import GetPeak= 0
DSS Import FillOption= 0

--- WOLFCK.g01 (geometry) ---

Geom Title=USGS 10m DEM
Program Version=4.10

River Reach=WOLFCK          ,Main
Reach XY= 30
     2011057.972      217513.706     2011179.048      217805.091
     2012023.318      218636.341     2012394.673      218558.737
     2012769.673      218720.195     2013532.173      218547.279
     2013651.053      218275.664     2014692.014      217655.936
     2014929.933      217767.384     2016038.634      217709.117
     2016305.924      218064.732     2016541.767      218142.884
     2016623.619       217981.03     2017017.154      218295.951
     2017315.426      218244.158     2017628.497      218363.004
     2018201.132      218220.077     2018487.439      218559.818
     2018873.649      218237.619     2019168.993      218314.766
     2019448.649      218956.369     2019877.121      219425.119
     2020457.323      219810.642     2021201.427      220100.813
     2021686.358      219770.049     2021911.149      219449.425
     2022458.371      219418.175     2023120.382      219038.724
     2023570.177      219459.147     2024065.678      219695.465

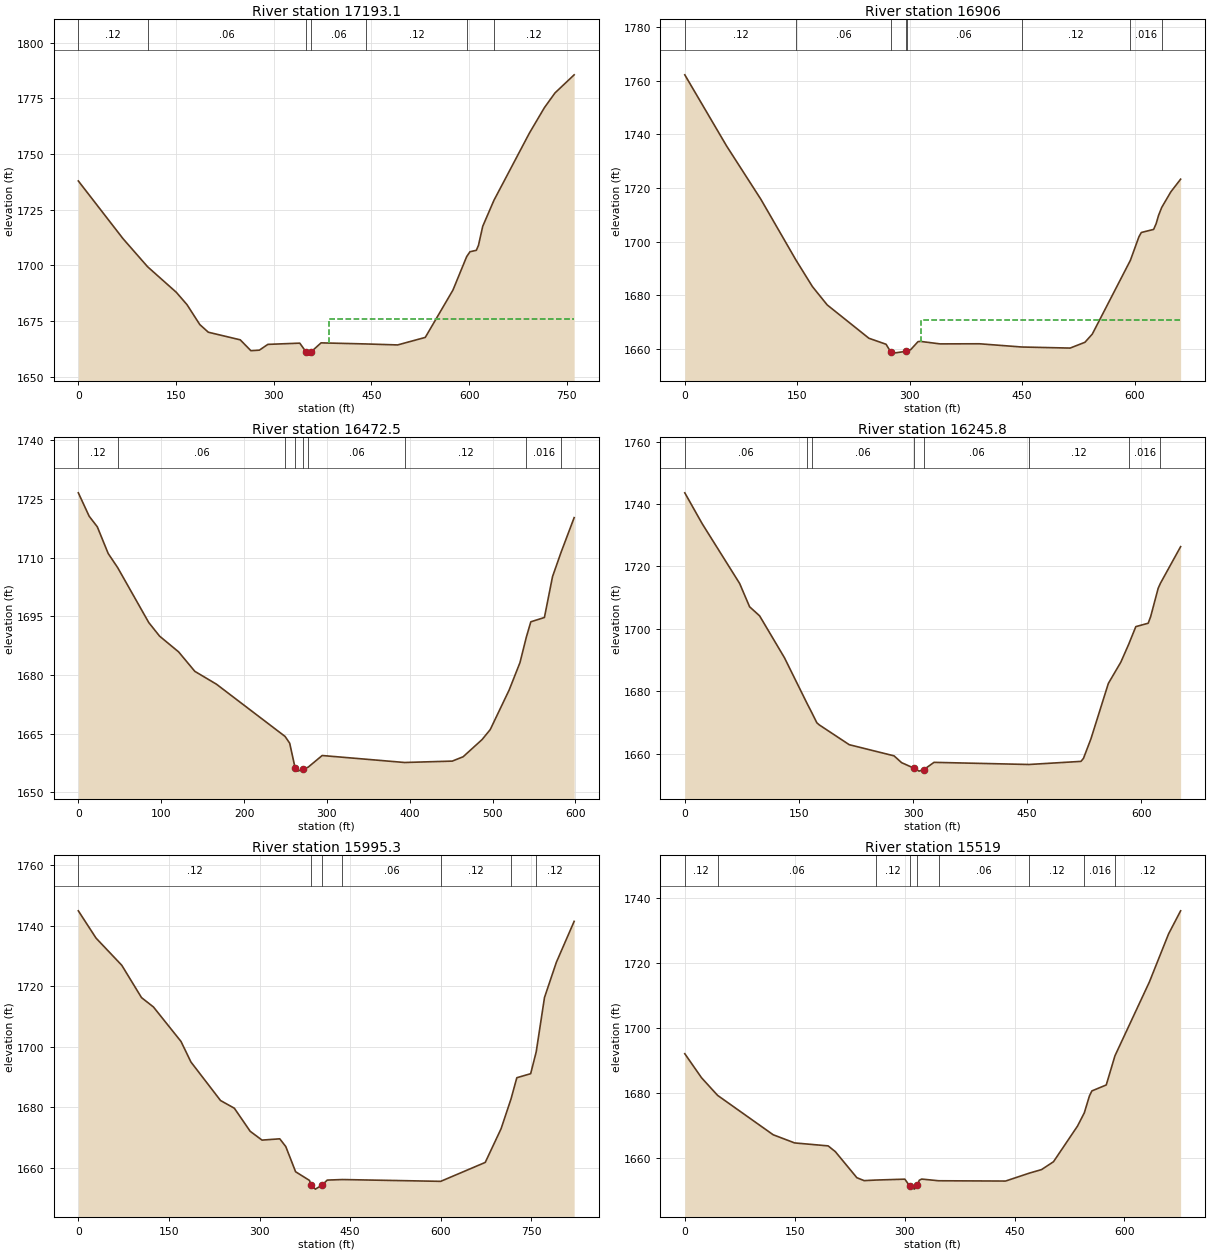
Type RM Length L Ch R = 1 ,17193.1 ,288,287.2,285
XS GIS Cut Line= 3
     2010846.283      217860.109       2010961.3      217693.008
     2011396.052      217342.469
#Sta/Elev= 30
       0 1737.91    68.7 1711.95  106.381699.361   150.5 1687.87   166.9 1682.33
   186.5  1673.4   199.6 1669.96   248.6 1666.54   264.9 1661.68     278 1661.91
     291  1664.5     340 1665.05   349.8 1661.05   353.1 1660.57     358  1661.3
   372.7 1665.18     4421664.689   490.3 1664.25   532.7 1667.63   575.2 1688.89
  596.251703.912   601.3  1706.1   611.1 1706.76   614.4    1709   620.9 1717.52
  638.111729.198   692.7 1759.47   715.6 1770.82   731.9 1777.46   761.3 1785.58
#Mann= 7 ,-1 , 0
       0     .12       0  106.38     .06       0   349.8    .045       0
     358     .06       0     442     .12       0  596.25    .016       0
  638.11     .12       0
#XS Ineff= 2 , 0
                          384.85         1675.83
Permanent Ineff=
       F       F
Bank Sta=349.8,358
XS Rating Curve= 0 ,0
Exp/Cntr=0.3,0.1

Type RM Length L Ch R = 1 ,16906   ,434.8,433.4,429.4
XS GIS Cut Line= 2
     2011000.219      218029.969     2011489.802      217585.524
#Sta/Elev= 30
       0 1762.15    55.6 1735.72   101.5 1715.79  148.271693.176   170.2 1683.31
   189.9 1676.49   245.5 1664.08   268.4 1661.84     275  1658.8   278.2 1658.54
   294.9  1659.2  295.831659.243   301.2 1659.83     311 1662.81   314.2 1662.91
   340.4 1661.98   392.8 1662.02  449.451660.818   513.9 1660.42   533.6 1662.58
   543.4 1665.62  594.221693.097   605.6 1701.86   608.8 1703.45   625.2  1704.6
   628.5  1706.7   631.8 1709.83  635.981712.778   648.1 1718.56   661.2  1723.3
#Mann= 8 ,-1 , 0
       0     .12       0  148.27     .06       0     275    .045       0
   294.9     .12       0  295.83     .06       0  449.45     .12       0
  594.22    .016       0  635.98     .12       0
#XS Ineff= 2 , 0
                          315.38            1671
Permanent Ineff=
       F       F
Bank Sta=275,294.9
XS Rating Curve= 0 ,0
Exp/Cntr=0.3,0.1

Type RM Length L Ch R = 1 ,16472.5 ,227,226.8,225.7
XS GIS Cut Line= 2
     2011354.386      218325.108     2011743.275      217870.247
#Sta/Elev= 30
       0 1726.54    13.1 1720.55    22.9 1717.86      36 1711.05   47.571707.394
      85 1693.39    98.1 1689.91     121  1685.9   140.6 1680.92   166.8 1677.62
  249.551664.278   255.1 1662.55   261.6 1656.26   264.9 1655.42   270.8 1655.92
  277.361656.429   294.3 1659.41  393.771657.626   451.3 1657.98   464.4 1659.09
   487.3 1663.49   497.1 1666.03     520 1676.17     533 1683.15  540.571689.575
   546.1 1693.58   562.5 1694.68   572.3 1705.13  582.581711.329   598.4  1720.2
#Mann= 9 ,-1 , 0
       0     .12       0   47.57     .06       0  249.55     .12       0
   261.6    .045       0   270.8     .12       0  277.36     .06       0
  393.77     .12       0  540.57    .016       0  582.58     .12       0
Bank Sta=261.6,270.8
XS Rating Curve= 0 ,0
Exp/Cntr=0.3,0.1

Type RM Length L Ch R = 1 ,16245.8 ,247,250.4,238.8
XS GIS Cut Line= 2
     2011494.143       218516.08     2011903.865      218009.135
#Sta/Elev= 30
       0 1743.58    22.9 1733.68    72.1 1714.56    85.2 1707.09    98.3 1704.21
     131 1690.79  160.871676.084   166.81673.284   173.6 1669.96   176.9 1669.26
   216.2 1662.94   275.1 1659.37     285 1657.19   301.3 1655.42   307.9 1654.48
   314.4 1654.99   327.6 1657.29  452.461656.604   520.8  1657.6   524.1 1658.58
   533.9 1664.82   556.8 1682.56   573.2 1689.37  583.521695.077   592.9 1700.74
   609.2 1701.83   612.5 1704.03   622.3 1713.03  625.311714.645   651.8 1726.35
#Mann= 8 ,-1 , 0
       0     .06       0  160.87     .12       0   166.8     .06       0
   301.3    .045       0   314.4     .06       0  452.46     .12       0
  583.52    .016       0  625.31     .12       0
Bank Sta=301.3,314.4
XS Rating Curve= 0 ,0
Exp/Cntr=0.3,0.1

Type RM Length L Ch R = 1 ,15995.3 ,478.6,476.4,472.2
XS GIS Cut Line= 2
     2011541.886      218739.604     2012097.441      218135.438
#Sta/Elev= 30
       0 1744.87    29.4 1735.84    71.9 1726.89   104.6  1716.2   124.3 1713.12
     170 1701.71   186.4 1694.94   235.4 1682.21   258.3 1679.66   284.5 1672.04
   304.1 1669.13   333.5 1669.56   343.4    1667   359.7 1658.68   382.6 1655.82
   385.9 1654.14   392.4 1652.94   403.5 1654.27     412 1655.92  437.011656.104
  599.881655.512   673.6 1661.76   699.8 1672.88  716.251682.718   725.9 1689.74
   748.8 1691.07  757.981698.279   771.7 1716.24   791.3 1727.85   820.8 1741.39
#Mann= 7 ,-1 , 0
       0     .12       0   385.9    .045       0   403.5     .12       0
  437.01     .06       0  599.88     .12       0  716.25    .016       0
  757.98     .12       0
Bank Sta=385.9,403.5
XS Rating Curve= 0 ,0
Exp/Cntr=0.3,0.1

Type RM Length L Ch R = 1 ,15519   ,402,404.1,398.9
XS GIS Cut Line= 3
     2012024.668      218901.776     2012102.793      218736.845
     2012330.658      218298.477
#Sta/Elev= 30
       0 1692.06    22.8 1684.66   44.781679.217   120.6 1667.08   149.9 1664.56
   195.6 1663.65   205.4 1661.88   234.8 1653.84   244.7 1652.94  260.541653.114
   300.3 1653.39   306.8 1651.31   313.4 1650.32   317.5 1651.55   319.9 1653.03
   323.2 1653.42  346.431652.898   437.7 1652.81  470.281655.261   486.8 1656.34
   503.1 1658.76   535.9 1669.76  545.151673.828   552.2 1679.07   555.5 1680.59
   575.1 1682.43  586.991691.423     634 1714.19   660.2 1729.02   676.6 1736.11
#Mann= 9 ,-1 , 0
       0     .12       0   44.78     .06       0  260.54     .12       0
   306.8    .045       0   317.5     .12       0  346.43     .06       0
  470.28     .12       0  545.15    .016       0  586.99     .12       0
Bank Sta=306.8,317.5
XS Rating Curve= 0 ,0
Exp/Cntr=0.3,0.1

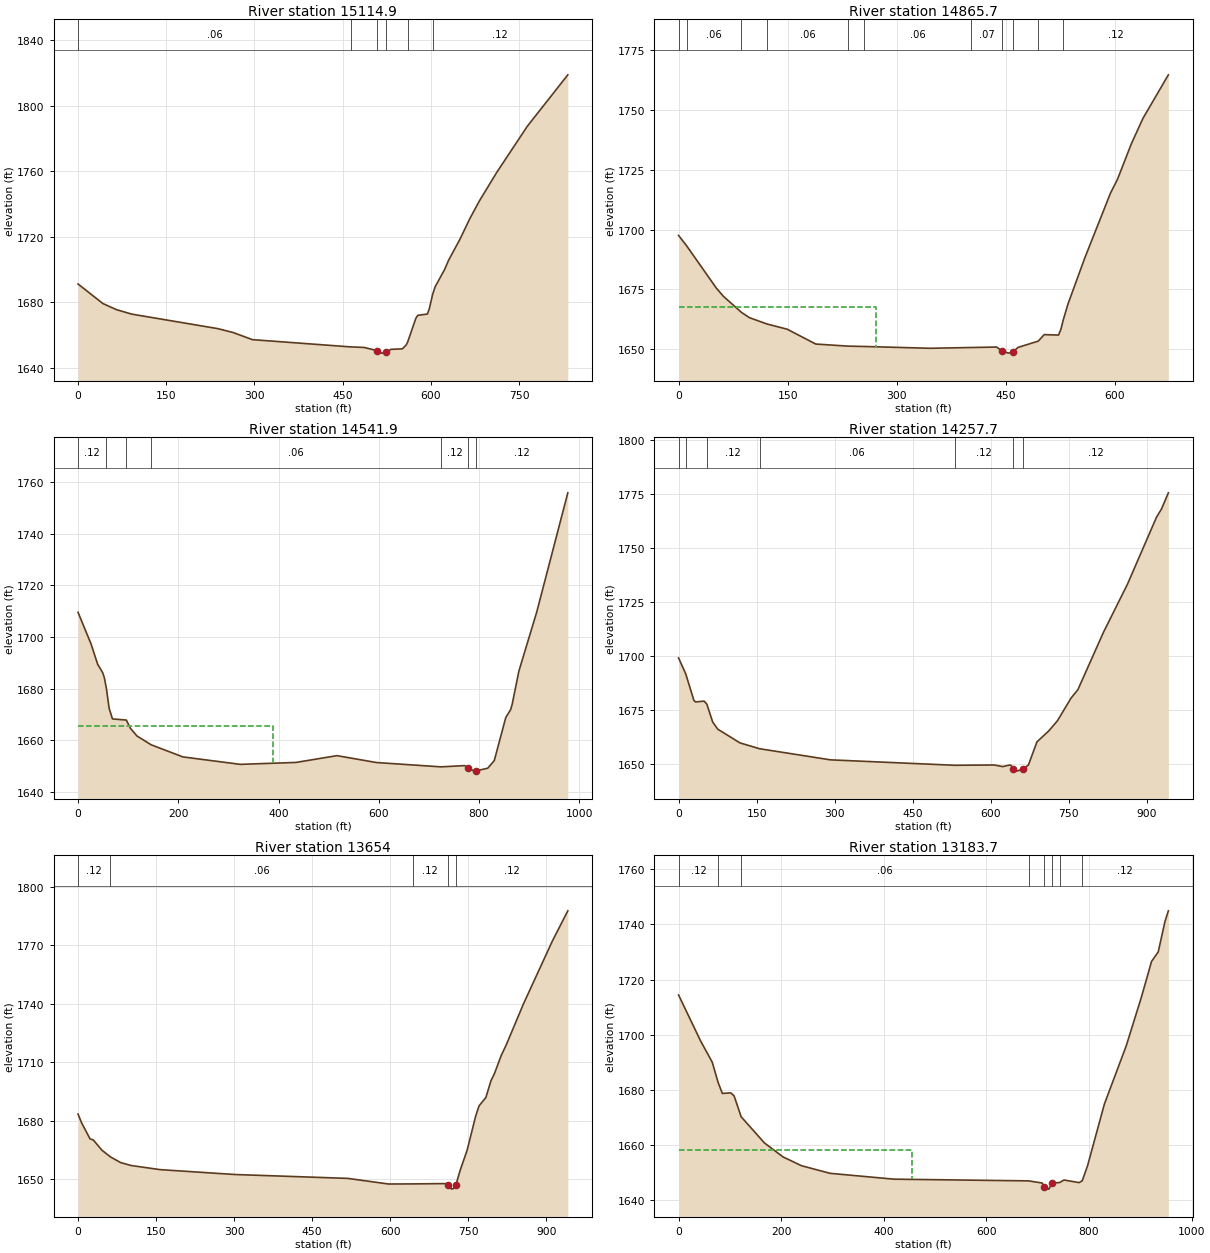
Type RM Length L Ch R = 1 ,15114.9 ,252.9,249.3,243
XS GIS Cut Line= 3
     2012499.929        219125.3     2012413.123      218845.352
     2012628.691      218350.715
#Sta/Elev= 30
       0 1691.21    42.3 1679.25    65.1 1675.55    91.2  1672.8   237.7 1663.92
   263.8 1661.54   296.4  1657.2  463.751652.758     486 1652.44     509 1650.47
   515.5 1648.96     524 1649.43   531.8 1651.27   551.4 1651.57     558 1653.99
   560.41655.715   574.3  1670.2   577.6 1672.06     594 1672.84   597.2 1676.04
  602.811684.773     607 1689.38   623.4 1700.19   629.9 1705.61   649.5 1718.68
   665.9    1731   682.2 1741.84   711.7 1759.29     764 1787.64   832.7 1818.99
#Mann= 6 ,-1 , 0
       0     .06       0  463.75     .12       0     509    .045       0
     524     .12       0   560.4    .016       0  602.81     .12       0
Bank Sta=509,524
XS Rating Curve= 0 ,0
Exp/Cntr=0.3,0.1

Type RM Length L Ch R = 1 ,14865.7 ,340,323.8,305.7
XS GIS Cut Line= 4
     2012606.266      219142.661     2012660.519      219021.133
     2012738.644      218589.276     2012742.984      218487.279
#Sta/Elev= 30
       0 1697.55   11.011693.244    51.9 1675.53    61.7 1672.07   86.581665.343
    97.4 1663.15   121.41660.504   149.5  1658.3   188.8 1652.09   233.31651.216
  255.431651.073     346 1650.32  402.37 1650.64   437.7 1650.83   445.3 1649.15
     454 1648.29   460.3 1648.88   467.2 1650.69  494.891653.314   503.2 1656.04
   522.8 1655.84   526.1 1658.24  529.551662.399   535.9 1668.88   558.8 1687.97
   594.3 1715.23   603.9 1720.99     623 1735.86     639 1746.54     674 1764.78
#Mann= 11 ,-1 , 0
       0     .12       0   11.01     .06       0   86.58    .016       0
   121.4     .06       0   233.3     .12       0  255.43     .06       0
  402.37     .07       0   445.3    .045       0   460.3     .12       0
  494.89    .016       0  529.55     .12       0
#XS Ineff= 2 , 0
          272.24 1667.67
Permanent Ineff=
       F       F
Bank Sta=445.3,460.3
XS Rating Curve= 0 ,0
Exp/Cntr=0.3,0.1

Type RM Length L Ch R = 1 ,14541.9 ,284,284.2,283.3
XS GIS Cut Line= 3
     2013422.238      219344.484     2012975.189      218602.297
     2012970.849      218491.619
#Sta/Elev= 30
       0 1709.55    26.2  1697.2    39.2 1689.41      49 1686.26    52.3 1684.42
   56.57 1680.14    62.1 1672.36    68.7  1668.3   96.391667.859   104.6 1664.64
   117.7 1661.68  145.921658.287   209.2  1653.6   323.7 1650.72   434.8 1651.46
   516.6 1654.09   595.1 1651.43  724.16 1649.75   771.6 1650.23     779 1649.18
   791.2  1648.1     794 1648.19   817.4 1649.23   830.5 1652.19   853.4 1668.82
   863.2 1671.92   866.4 1674.13   879.5 1686.74   915.3 1709.72   977.2 1755.76
#Mann= 7 ,-1 , 0
       0     .12       0   56.57    .016       0   96.39     .12       0
  145.92     .06       0  724.16     .12       0     779    .045       0
     794     .12       0
#XS Ineff= 2 , 0
          388.36 1665.43
Permanent Ineff=
       F       F
Bank Sta=779,794
XS Rating Curve= 0 ,0
Exp/Cntr=0.3,0.1

Type RM Length L Ch R = 1 ,14257.7 ,600.2,603.7,602.2
XS GIS Cut Line= 2
     2013621.747      219157.573     2013128.691       218355.49
#Sta/Elev= 30
       0 1698.99   13.69 1691.67    29.5 1679.29    32.8 1678.62    49.2    1679
   54.371677.571    65.6 1669.31    75.4 1665.99   118.1 1659.65  155.66 1656.96
     292 1651.81  530.881649.292   606.9 1649.43   623.3 1648.68   636.4 1649.42
   639.7 1649.12     643 1647.62   649.5 1646.59   661.5 1647.43   672.5 1649.44
   688.9 1660.14   711.9 1665.28   728.3 1669.91   754.5 1680.42   767.6 1684.31
   816.8 1710.88   862.8 1733.07   918.6 1764.08   928.4 1767.98   941.5 1775.41
#Mann= 7 ,-1 , 0
       0     .12       0   13.69    .016       0   54.37     .12       0
  155.66     .06       0  530.88     .12       0     643    .045       0
   661.5     .12       0
Bank Sta=643,661.5
XS Rating Curve= 0 ,0
Exp/Cntr=0.3,0.1

Type RM Length L Ch R = 1 ,13654   ,468.9,470.3,470
XS GIS Cut Line= 2
      2014040.15      218880.663     2013547.094       218078.58
#Sta/Elev= 30
       0 1683.48     6.6 1679.17      23 1670.82    29.5 1670.19    45.9    1665
    62.3 1661.55      82 1658.64   101.7 1657.17   157.5 1655.04   301.8 1652.53
   518.3 1650.55   597.1 1647.67     643 1647.72   705.3 1647.89   711.4 1646.97
   718.4 1645.05   721.7 1645.41   726.4 1647.26   734.8 1654.86     748 1665.02
   764.4 1682.46   770.9  1687.7     784 1691.99   793.9 1700.66   800.4 1704.17
   813.6 1713.57   823.4 1719.08   856.2  1739.9     912 1772.23   941.5 1787.58
#Mann= 5 ,-1 , 0
       0     .12       0    62.3     .06       0     643     .12       0
   711.4    .045       0   726.4     .12       0
Bank Sta=711.4,726.4
XS Rating Curve= 0 ,0
Exp/Cntr=0.3,0.1

Type RM Length L Ch R = 1 ,13183.7 ,388.2,391.7,390.7
XS GIS Cut Line= 2
     2014448.136      218696.635     2013958.552      217877.191
#Sta/Elev= 30
       0 1714.42    42.6 1697.88    65.6 1690.06    77.21682.627    85.3 1678.73
   101.7 1678.93   108.2 1677.85  121.981670.262   167.3 1660.79   203.4 1655.73
   239.5 1652.52   295.2 1649.76   419.9 1647.64     6821647.021   708.5 1646.25
   713.1 1644.95   721.7 1644.03   728.1 1646.27  742.47  1646.4   751.2 1647.34
   780.7 1646.39  786.711647.056   797.1  1652.5   829.9 1674.87   872.6 1696.05
   902.1 1713.67   921.8 1726.57   934.9 1730.07     948 1741.08   954.6 1744.94
#Mann= 8 ,-1 , 0
       0     .12       0    77.2    .016       0  121.98     .06       0
     682     .12       0   713.1    .045       0   728.1     .12       0
  742.47     .06       0  786.71     .12       0
#XS Ineff= 2 , 0
          455.62 1658.29
Permanent Ineff=
       F       F
Bank Sta=713.1,728.1
XS Rating Curve= 0 ,0
Exp/Cntr=0.3,0.1

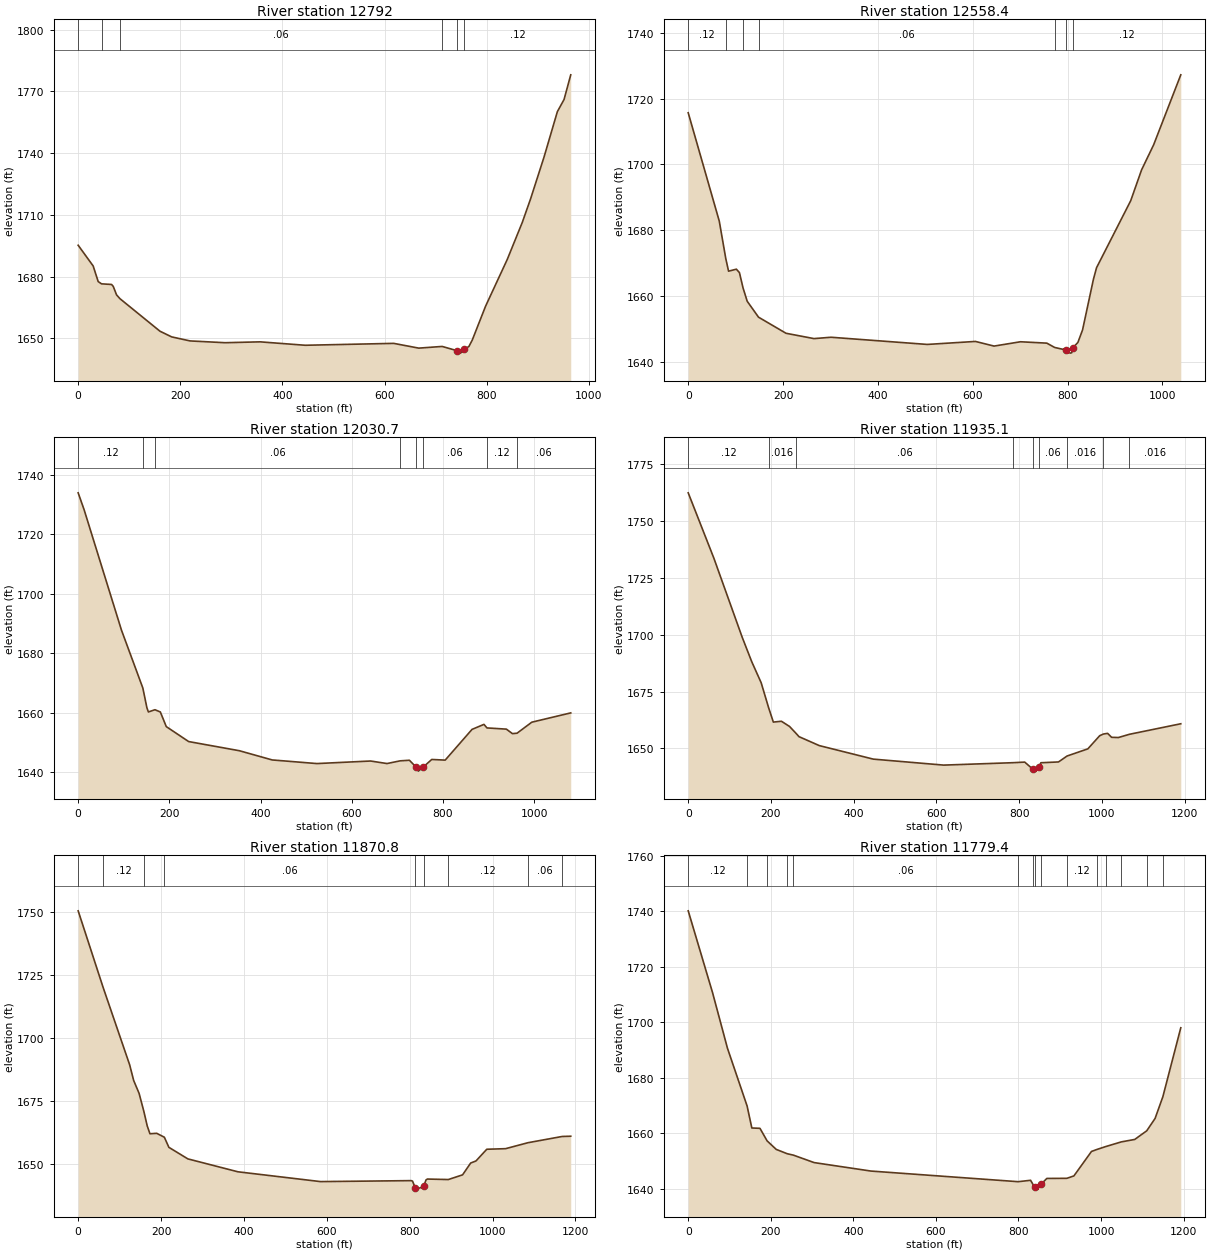
Type RM Length L Ch R = 1 ,12792   ,232.7,233.6,232.7
XS GIS Cut Line= 2
     2014678.247      218519.731     2014257.305      217651.733
#Sta/Elev= 30
       0 1695.24    29.4 1685.17    39.2  1677.6    45.8 1676.49    65.4 1676.19
    68.7 1675.26    75.2 1671.13    81.8 1669.29   160.2 1653.48   183.1 1650.72
   219.1 1648.76   287.8 1647.89   356.4 1648.31   444.7 1646.65     618 1647.57
   667.1 1645.26   712.9 1646.08   741.3 1644.06   748.9 1642.83   756.3 1644.75
   765.2 1646.04   771.8 1649.16   797.9 1665.63   840.4 1688.36   869.8 1706.34
   886.2 1717.89   912.4  1738.1   938.5 1760.14   951.6 1766.06   964.7 1778.04
#Mann= 6 ,-1 , 0
       0     .12       0    45.8    .016       0    81.8     .06       0
   712.9     .12       0   741.3    .045       0   756.3     .12       0
Bank Sta=741.3,756.3
XS Rating Curve= 0 ,0
Exp/Cntr=0.3,0.1

Type RM Length L Ch R = 1 ,12558.4 ,518,527.7,533
XS GIS Cut Line= 3
      2014892.58      218467.469     2014485.172      217602.731
     2014412.255      217563.668
#Sta/Elev= 30
       0 1715.69    65.5 1682.79   79.231671.415    85.1 1667.59   101.5  1668.2
     108 1667.16  115.591662.527   124.4 1658.46  148.241653.628   206.2 1648.74
   265.2 1647.12   301.2 1647.53   504.1 1645.35   605.6 1646.26   644.9 1644.85
   700.6 1646.16   756.2 1645.74  772.641644.433   796.4 1643.66   805.3 1642.71
   808.6 1642.82   811.4 1644.39   821.7 1645.97   831.5 1649.77   854.4 1665.13
     861 1668.65     933 1688.98   955.9 1698.34   981.4 1705.97  1038.6 1727.21
#Mann= 7 ,-1 , 0
       0     .12       0   79.23    .016       0  115.59     .12       0
  148.24     .06       0  772.64     .12       0   796.4    .045       0
   811.4     .12       0
Bank Sta=796.4,811.4
XS Rating Curve= 0 ,0
Exp/Cntr=0.3,0.1

Type RM Length L Ch R = 1 ,12030.7 ,97.1,95.6,94.7
XS GIS Cut Line= 4
     2014991.973      218481.792     2015065.757      218342.903
     2014987.632      217637.608     2014972.441      217424.934
#Sta/Elev= 30
       0 1733.94    13.1 1728.23      95 1687.75  141.831668.295   150.7 1661.68
     154 1660.26   168.41661.004   180.2 1660.25   193.2 1655.33   242.3  1650.3
   353.5 1647.22   425.4 1644.12   523.5  1642.9   641.2 1643.76   677.2 1642.91
  706.081643.818   726.3 1644.02   741.1  1641.7   745.9 1640.36   756.1 1641.66
   775.3 1644.28   804.8 1644.06   863.6 1654.39   889.8 1656.08  896.451654.885
     939 1654.48   952.2 1652.97  962.351653.107   994.8 1656.82  1080.1 1659.94
#Mann= 8 ,-1 , 0
       0     .12       0  141.83    .016       0   168.4     .06       0
  706.08     .12       0   741.1    .045       0   756.1     .06       0
  896.45     .12       0  962.35     .06       0
Bank Sta=741.1,756.1
XS Rating Curve= 0 ,0
Exp/Cntr=0.3,0.1

Type RM Length L Ch R = 1 ,11935.1 ,63.6,64.3,64.3
XS GIS Cut Line= 5
     2015045.358      218533.441     2015184.247      218335.524
     2015080.948      217657.139     2015007.164      217607.226
     2014998.483      217433.615
#Sta/Elev= 30
       0 1762.46    62.1 1733.66   130.7  1698.8   153.6 1688.12   176.4 1678.85
  194.451667.847   205.8 1661.54   225.4  1661.9   245.1  1659.6  260.971656.517
   267.9 1655.12   316.9 1651.19   447.6 1645.23   617.6  1642.6  785.32 1643.66
   813.6 1643.92   832.4 1640.95   839.8 1639.95   847.4 1641.75   852.8 1643.64
   895.3 1643.99  915.881646.595   966.2 1649.75   994.8 1655.53 1003.521656.263
  1013.9 1656.58  1023.6 1654.84    1040 1654.74  1066.61656.158  1190.9  1660.8
#Mann= 9 ,-1 , 0
       0     .12       0  194.45    .016       0  260.97     .06       0
  785.32     .12       0   832.4    .045       0   847.4     .06       0
  915.88    .016       0 1003.52     .12       0  1066.6    .016       0
Bank Sta=832.4,847.4
XS Rating Curve= 0 ,0
Exp/Cntr=0.3,0.1

Type RM Length L Ch R = 1 ,11870.8 ,90.2,91.4,92.1
XS GIS Cut Line= 5
     2015103.952       218524.76     2015242.841      218326.844
     2015141.712      217641.948     2015065.757      217598.545
     2015034.507      217434.483
#Sta/Elev= 30
       0 1750.59      601720.289   124.2 1689.48     134 1683.21     147 1678.14
  158.611670.896   166.6 1665.22   173.2 1662.09   189.5 1662.27  207.951660.718
   218.9  1656.7   264.6 1652.12   385.5 1646.99   584.7  1643.1   803.5 1643.48
   806.8  1643.3   813.3 1640.65   816.5 1640.11   833.5 1641.16   839.4 1643.77
   842.7 1644.11  893.151643.914   927.6 1645.78   947.1 1650.46     960  1651.3
     986 1655.94  1031.4 1656.17 1085.44 1658.54 1167.971661.014  1188.6 1661.11
#Mann= 9 ,-1 , 0
       0     .06       0      60     .12       0  158.61    .016       0
  207.95     .06       0   813.3    .045       0   833.5     .06       0
  893.15     .12       0 1085.44     .06       0 1167.97     .12       0
Bank Sta=813.3,833.5
XS Rating Curve= 0 ,0
Exp/Cntr=0.3,0.1

Type RM Length L Ch R = 1 ,11779.4 ,214.2,216.3,216.8
XS GIS Cut Line= 3
     2015146.052      218529.535     2015306.643       218301.67
     2015211.157      217392.382
#Sta/Elev= 30
       0 1740.21      59 1710.72    95.1  1690.7  142.631669.908   154.1 1661.98
   173.8 1661.85  191.031657.351   213.2 1654.26  240.051652.694  254.831652.191
     305 1649.51   442.6 1646.46  799.111642.631   829.3 1643.13   836.11641.394
   839.2 1640.55   845.7 1639.95   854.2 1641.63   868.6  1643.8  917.141643.844
   934.2 1644.71   976.8 1653.52  990.521654.266 1011.71  1655.3 1048.82 1656.96
  1081.6 1657.85 1110.621660.964  1130.8  1665.4 1149.661673.224  1193.1 1698.08
#Mann= 15 ,-1 , 0
       0     .12       0  142.63    .016       0  191.03     .06       0
  240.05     .12       0  254.83     .06       0  799.11     .12       0
   836.1     .06       0   839.2    .045       0   854.2     .06       0
  917.14     .12       0  990.52     .08       0 1011.71     .06       0
 1048.82     .12       0 1110.62     .06       0 1149.66     .12       0
Bank Sta=839.2,854.2
XS Rating Curve= 0 ,0
Exp/Cntr=0.3,0.1

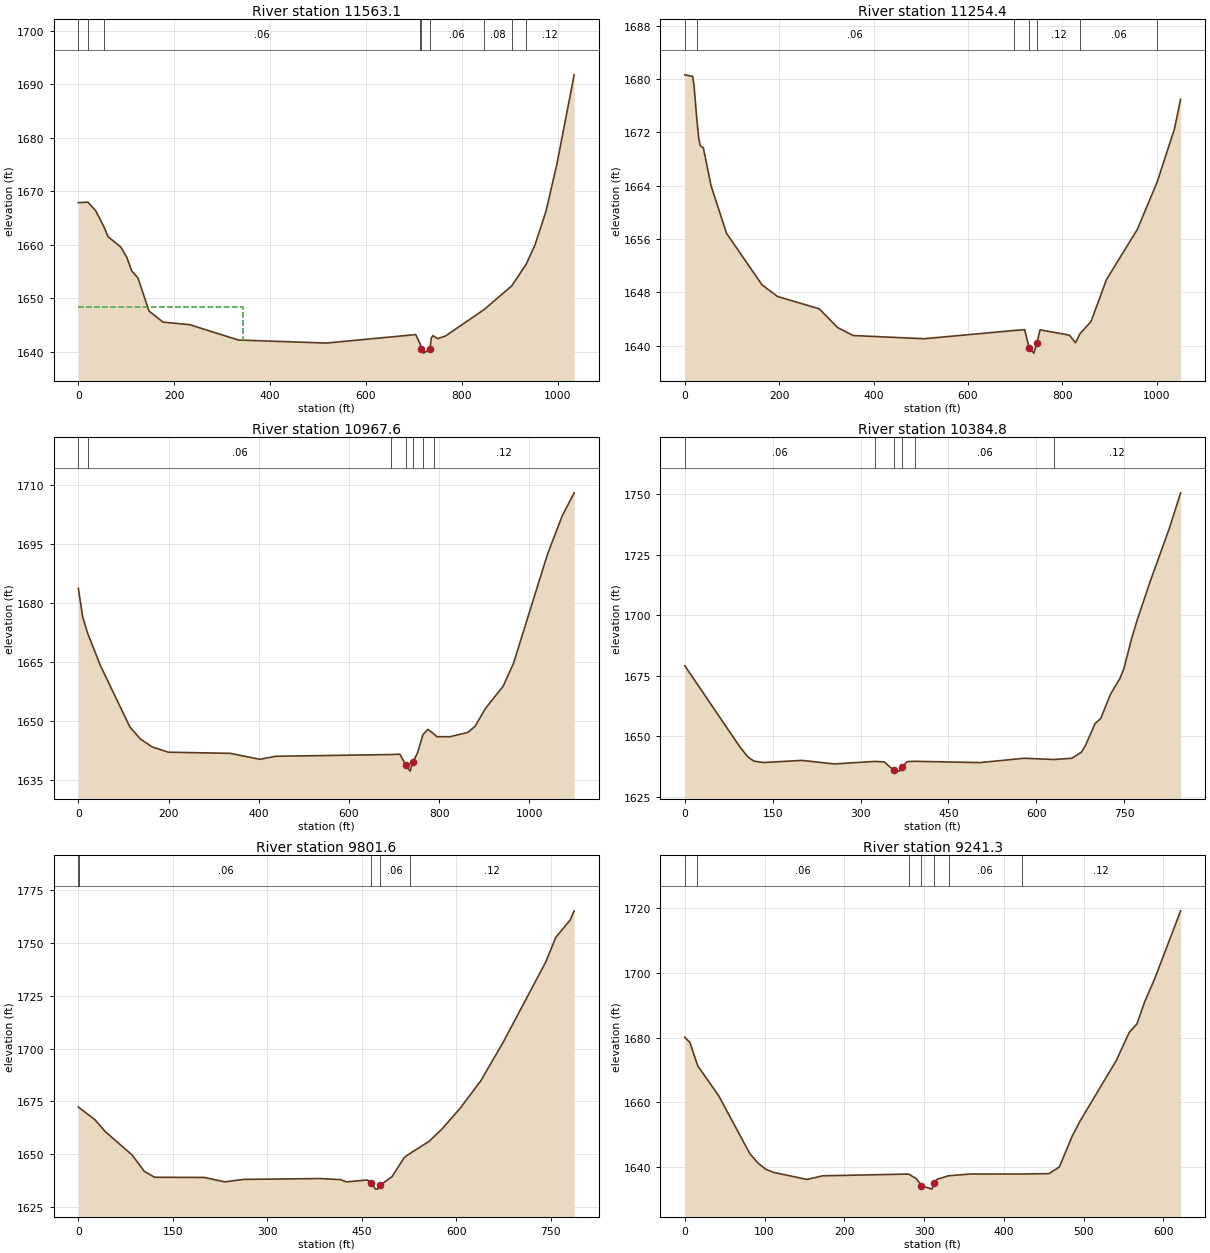
Type RM Length L Ch R = 1 ,11563.1 ,307.2,308.7,309
XS GIS Cut Line= 2
     2015492.841      218441.861     2015445.098      217408.875
#Sta/Elev= 30
       0 1667.88   19.891667.988      36 1666.42    53.41663.386    62.2 1661.51
    88.4 1659.62   101.4 1657.63   111.3 1655.14   124.4 1653.82   147.3 1647.66
   176.7 1645.58   232.3  1645.1   333.8 1642.24     517 1641.67   703.6 1643.25
  713.351641.407  715.58 1640.51   719.9 1639.79     733 1640.47   736.3 1642.62
   739.6 1643.05   749.4 1642.49   765.8 1642.99  846.651647.948   903.91652.345
  933.931656.376   952.3 1659.96   975.2 1666.24   998.1 1675.07  1034.1 1691.76
#Mann= 9 ,-1 , 0
       0    .016       0   19.89     .12       0    53.4     .06       0
  713.35     .12       0  715.58    .045       0     733     .06       0
  846.65     .08       0   903.9     .06       0  933.93     .12       0
#XS Ineff= 2 , 0
          343.92 1648.42
Permanent Ineff=
       F       F
Bank Sta=715.58,733
XS Rating Curve= 0 ,0
Exp/Cntr=0.3,0.1

Type RM Length L Ch R = 1 ,11254.4 ,285.7,286.8,286.7
XS GIS Cut Line= 2
     2015762.372      218447.069     2015764.542      217396.722
#Sta/Elev= 30
       0 1680.64    16.4 1680.41    19.6 1679.04   25.071674.342    29.4 1671.18
    32.7 1670.02    39.3 1669.68    55.6 1664.02    88.4 1656.87   163.6 1649.14
   196.3  1647.4   284.7 1645.55   323.9 1642.73   356.7 1641.54   507.2 1641.06
  697.381642.292   719.9 1642.42   729.7 1639.68   739.5  1638.9     746 1640.45
   752.6 1642.39   814.8  1641.6   827.8 1640.45  837.241641.818   860.6 1643.64
   893.3 1649.93   958.7 1657.46 1000.531664.529  1037.3 1672.52  1050.4 1676.98
#Mann= 7 ,-1 , 0
       0    .016       0   25.07     .06       0  697.38     .12       0
   729.7    .045       0     746     .12       0  837.24     .06       0
 1000.53     .12       0
Bank Sta=729.7,746
XS Rating Curve= 0 ,0
Exp/Cntr=0.3,0.1

Type RM Length L Ch R = 1 ,10967.6 ,576.6,582.8,566
XS GIS Cut Line= 3
     2016011.938      218442.729      2016044.49      217563.823
     2016224.611      217437.955
#Sta/Elev= 30
       0 1683.79     9.8 1676.47   20.741672.341      49 1664.15   114.4 1648.55
   137.3 1645.53   163.5  1643.5   199.4 1642.15   336.8 1641.86   402.2 1640.34
   438.1 1641.12  693.571641.553   712.8 1641.65   726.5 1638.81   735.6 1637.34
   741.5  1639.6     752 1641.99  763.951646.614   774.9 1647.95  787.621646.878
   794.5 1646.09   823.9 1646.08   863.2 1647.18   879.5 1648.72   902.5 1653.26
   941.8 1658.92   964.8 1664.76  1040.2  1692.5    1073 1702.28  1099.2 1708.06
#Mann= 7 ,-1 , 0
       0     .12       0   20.74     .06       0  693.57     .12       0
   726.5    .045       0   741.5     .12       0  763.95     .06       0
  787.62     .12       0
Bank Sta=726.5,741.5
XS Rating Curve= 0 ,0
Exp/Cntr=0.3,0.1

Type RM Length L Ch R = 1 ,10384.8 ,576.9,583.2,581.1
XS GIS Cut Line= 3
     2016335.653      218432.618     2016383.609      217678.251
     2016443.505      217610.543
#Sta/Elev= 30
       0  1679.1    94.9  1645.3     108 1641.41   117.8 1639.76   134.2 1639.15
   199.6 1640.04   255.2 1638.58  324.351639.613   340.3 1639.42   356.3 1636.04
   366.5 1635.61   371.3 1637.36   379.6 1639.54  392.631639.661   503.9 1639.13
   579.2 1640.92  630.111640.403     661 1640.94   677.4 1643.54   683.9 1646.22
   700.3 1655.22   710.1  1657.4   726.4 1667.25   742.8 1673.91   749.3 1677.82
   762.4 1690.03     772 1697.86   794.6 1714.08   826.9 1735.72   846.3 1750.48
#Mann= 6 ,-1 , 0
       0     .06       0  324.35     .12       0   356.3    .045       0
   371.3     .12       0  392.63     .06       0  630.11     .12       0
Bank Sta=356.3,371.3
XS Rating Curve= 0 ,0
Exp/Cntr=0.3,0.1

Type RM Length L Ch R = 1 ,9801.6  ,552.7,560.3,557
XS GIS Cut Line= 3
     2016682.659      218482.709       2016725.9      217838.638
     2016821.487      217733.948
#Sta/Elev= 30
       0  1672.4    1.611671.985    26.2 1666.43    42.6  1660.8    85.2 1649.76
   104.9 1641.94   121.2 1639.16   199.9 1639.09   232.6 1636.99   262.1 1638.15
   383.4 1638.56   416.2 1638.05     426 1636.98   458.8 1637.89   465.3  1636.5
   471.8 1633.63   475.1 1633.56   479.4 1635.42   498.1 1639.46   517.7 1648.55
  526.091650.321     557 1656.17   576.7 1661.76   606.2 1671.75     639 1684.76
   674.5 1702.94   742.2 1740.95   758.3 1752.68   780.8 1760.72   787.3 1765.14
#Mann= 5 ,-1 , 0
       0     .12       0    1.61     .06       0   465.3    .045       0
   479.4     .06       0  526.09     .12       0
Bank Sta=465.3,479.4
XS Rating Curve= 0 ,0
Exp/Cntr=0.3,0.1

Type RM Length L Ch R = 1 ,9241.3  ,327.1,329.6,330.1
XS GIS Cut Line= 3
     2017010.801      218601.087     2017082.891       218087.72
     2017144.244      218004.743
#Sta/Elev= 30
       0  1680.2     6.5 1678.54   14.991672.219    16.3 1671.31    42.4 1662.12
    81.5 1644.21    91.3 1641.38   101.1 1639.41   110.8 1638.42   153.2  1636.2
   172.8 1637.33   280.61637.868   290.2 1636.46   296.7 1634.29   309.7 1633.21
     313 1634.98   316.3 1636.26  330.651637.344   358.6 1637.89  422.46 1637.88
   456.5 1638.01   469.5 1640.05   485.8 1649.66   495.6 1654.29     541 1673.01
   557.1 1681.65   566.8  1684.3   576.4 1691.05   589.4 1698.45   621.6 1719.27
#Mann= 7 ,-1 , 0
       0    .016       0   14.99     .06       0   280.6     .12       0
   296.7    .045       0     313     .12       0  330.65     .06       0
  422.46     .12       0
Bank Sta=296.7,313
XS Rating Curve= 0 ,0
Exp/Cntr=0.3,0.1

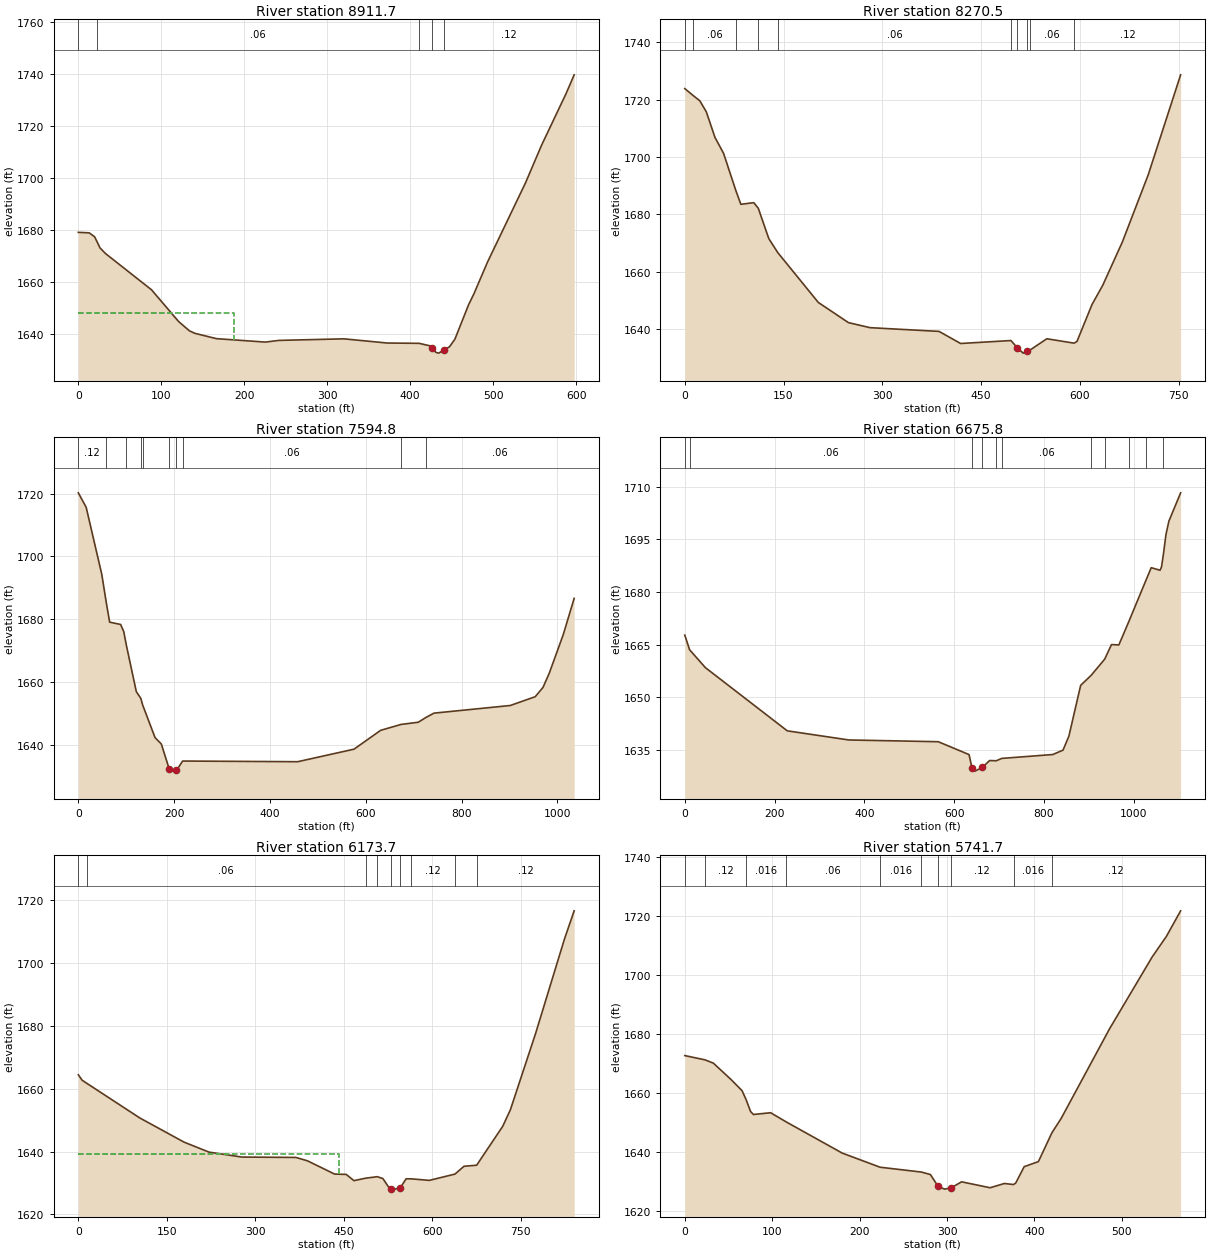
Type RM Length L Ch R = 1 ,8911.7  ,649.6,641.2,628.5
XS GIS Cut Line= 2
     2017278.937       218680.71     2017401.834      218095.811
#Sta/Elev= 30
       0 1679.05    13.1 1678.86    19.6 1677.36   21.931675.849    26.1 1673.08
    32.7  1670.9    88.2 1656.94   120.8 1644.74   133.9 1641.13   140.4 1640.17
   166.6 1638.11   225.4 1636.79   241.7 1637.44   320.1 1638.04   372.3 1636.43
   410.81636.311   424.6  1635.3   426.4 1634.59   431.1 1632.82   434.4 1632.54
   441.4 1633.83   447.4 1634.99     454 1637.94   470.3 1651.06   476.8 1655.33
   493.2 1667.56   538.9    1698   558.5 1712.66   587.9 1732.44   597.7 1739.71
#Mann= 5 ,-1 , 0
       0    .016       0   21.93     .06       0   410.8     .12       0
   426.4    .045       0   441.4     .12       0
#XS Ineff= 2 , 0
          187.22    1648
Permanent Ineff=
       F       F
Bank Sta=426.4,441.4
XS Rating Curve= 0 ,0
Exp/Cntr=0.3,0.1

Type RM Length L Ch R = 1 ,8270.5  ,665.5,675.6,682.1
XS GIS Cut Line= 4
      2017990.38      218769.397     2018011.214      218561.064
     2017912.039      218160.721     2017836.734      218053.251
#Sta/Elev= 30
       0 1723.88   13.211721.362    22.9  1719.6    32.7 1715.77    45.8 1706.87
    58.9 1701.29   77.211688.533    85.1 1683.52   104.7 1684.09  111.591682.157
   127.6 1671.54  141.281666.651   202.8 1649.28   248.6 1642.24   281.4 1640.49
   386.1 1639.19   418.9 1634.97  495.291636.002   504.9 1633.52   513.8 1631.61
   519.9 1632.29  524.061632.643   549.8 1636.62   591.31635.087   595.6 1635.69
   618.5 1648.59   634.9 1655.36   664.5 1670.37   703.8 1693.81     753 1728.68
#Mann= 10 ,-1 , 0
       0    .016       0   13.21     .06       0   77.21    .016       0
  111.59     .12       0  141.28     .06       0  495.29     .12       0
   504.9    .045       0   519.9     .12       0  524.06     .06       0
   591.3     .12       0
Bank Sta=504.9,519.9
XS Rating Curve= 0 ,0
Exp/Cntr=0.3,0.1

Type RM Length L Ch R = 1 ,7594.8  ,920.2,919,914.6
XS GIS Cut Line= 3
      2018334.13      218727.731     2018466.943      217990.751
     2018250.797      217803.251
#Sta/Elev= 30
       0 1720.26    16.4 1715.64      49 1694.23   57.881685.699    65.4 1679.02
    88.3 1678.29    94.8    1676  100.491671.501     121 1656.89  130.511654.676
  134.181652.654   160.2  1642.2   173.3 1640.16   189.9 1632.12   196.2 1631.52
   204.9 1631.74  217.751634.737   457.8 1634.52   575.5 1638.52   631.1 1644.53
  673.671646.411   709.6 1647.11  726.131648.677   742.3 1650.01   901.7 1652.45
   953.7 1655.25     970 1658.22     983 1662.73  1012.2 1675.03    1035  1686.6
#Mann= 10 ,-1 , 0
       0     .12       0   57.88    .016       0  100.49     .12       0
  130.51     .06       0  134.18     .12       0   189.9    .045       0
   204.9     .12       0  217.75     .06       0  673.67    .016       0
  726.13     .06       0
Bank Sta=189.9,204.9
XS Rating Curve= 0 ,0
Exp/Cntr=0.3,0.1

Type RM Length L Ch R = 1 ,6675.8  ,462.1,502.1,528.8
XS GIS Cut Line= 4
     2018828.805      218903.745     2019085.978      218587.399
     2019076.874      218070.776     2019220.254      217961.535
#Sta/Elev= 30
       0 1667.69   10.651663.535    45.7 1658.45   228.3 1640.42   365.3 1637.82
   564.7 1637.32   633.3 1633.65   639.9 1629.83   646.4 1628.94   662.8 1629.99
   679.1 1631.96  693.871631.892  706.041632.563   819.8 1633.67   842.6 1634.92
   855.7 1638.91   881.9 1653.38   905.41656.255  935.441660.845   950.6    1665
     967  1664.9   988.61671.372 1027.291683.302  1039.1 1686.91  1058.8 1686.18
    1062 1687.11 1066.041690.544  1071.9 1696.33  1078.4 1700.15  1104.6 1708.24
#Mann= 11 ,-1 , 0
       0    .016       0   10.65     .06       0   639.9    .045       0
   662.8     .06       0  693.87     .12       0  706.04     .06       0
   905.4     .12       0  935.44    .016       0   988.6     .12       0
 1027.29    .016       0 1066.04     .12       0
Bank Sta=639.9,662.8
XS Rating Curve= 0 ,0
Exp/Cntr=0.3,0.1

Type RM Length L Ch R = 1 ,6173.7  ,442.9,432,427.3
XS GIS Cut Line= 3
     2018894.894      218935.196     2019042.464      218748.564
      2019615.38      218561.932
#Sta/Elev= 30
       0 1664.45     6.5 1662.71   13.981661.778   104.3  1650.7   179.3 1643.01
   221.6 1639.84   277.2 1638.27   368.9 1638.15   388.6 1637.06   434.4 1632.86
   454.1 1632.75   467.2 1630.77  487.04 1631.55  506.76 1632.03   516.3 1631.43
   526.1  1628.7   530.8 1628.17   535.9 1628.07   545.8 1628.49   555.6 1631.36
  564.461631.339   594.9 1630.85   638.41632.851   653.8 1635.34  675.211635.679
   719.3 1648.02   732.4 1653.31     775 1677.51   824.1 1707.65   840.5  1716.6
#Mann= 9 ,-1 , 0
       0     .12       0   13.98     .06       0  487.04     .12       0
  506.76     .06       0   530.8    .045       0   545.8     .06       0
  564.46     .12       0   638.4    .016       0  675.21     .12       0
#XS Ineff= 2 , 0
          442.06  1639.4
Permanent Ineff=
       F       F
Bank Sta=530.8,545.8
XS Rating Curve= 0 ,0
Exp/Cntr=0.3,0.1

Type RM Length L Ch R = 1 ,5741.7  ,444,433.8,423.1
XS GIS Cut Line= 3
     2019279.009      219199.953     2019385.452      219054.726
     2019734.738      218887.453
#Sta/Elev= 30
       0 1672.65   23.06 1671.21    32.7 1670.08    52.4 1664.67    65.5 1660.74
   70.08 1657.75    75.3 1653.65    78.6 1652.65    98.2 1653.25  116.241650.097
   180.1 1639.55   223.41634.751   270.61633.111     281 1632.27   289.7 1628.29
   297.2 1627.31   304.7 1627.73   316.7 1629.79   349.3 1627.78   365.6 1629.22
  376.15 1628.87   378.6 1629.36   388.3 1634.93   404.6 1636.66  420.031646.438
   430.6  1651.3     486 1681.75   534.8 1706.16   551.1 1713.16   567.3  1721.8
#Mann= 10 ,-1 , 0
       0     .08       0   23.06     .12       0   70.08    .016       0
  116.24     .06       0   223.4    .016       0   270.6     .12       0
   289.7    .045       0   304.7     .12       0  376.15    .016       0
  420.03     .12       0
Bank Sta=289.7,304.7
XS Rating Curve= 0 ,0
Exp/Cntr=0.3,0.1