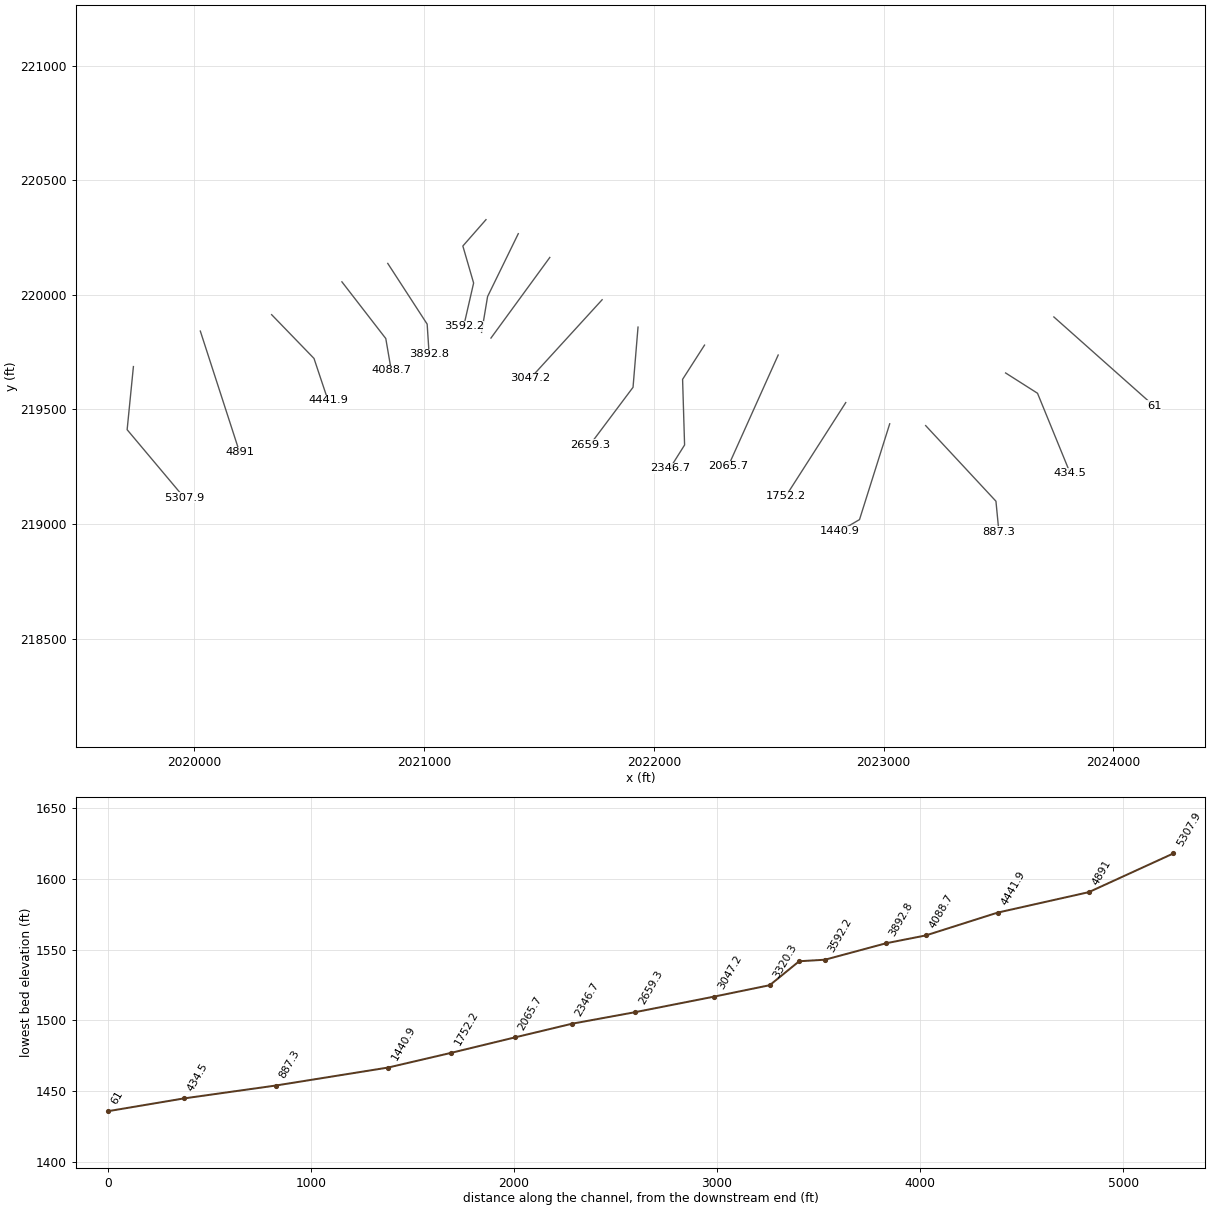
HEC-RAS study WOLFCK.prj: WOLFCK

--- WOLFCK.g01 (geometry) --- (continued)

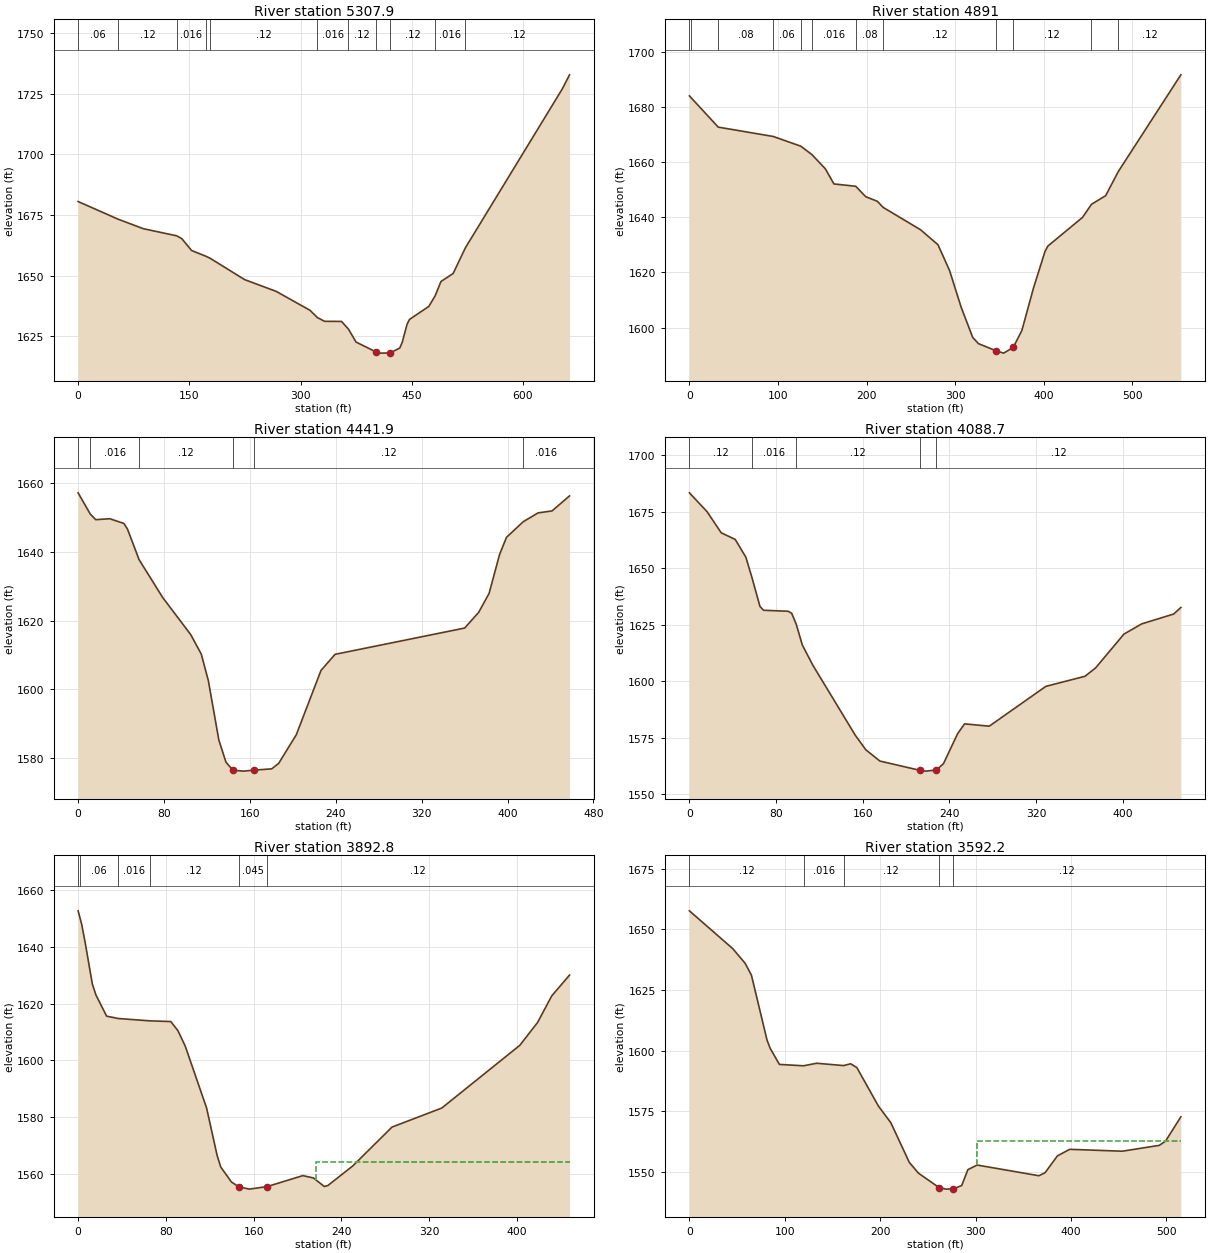
Type RM Length L Ch R = 1 ,5307.9  ,424.9,416.9,407.4
XS GIS Cut Line= 3
     2019734.601      219686.644     2019707.291      219411.264
      2019955.36      219115.401
#Sta/Elev= 30
       0 1680.59   53.731673.351    87.9 1669.41  133.151666.458     140 1665.26
     153 1660.43  172.461658.042  178.221657.195   224.6 1648.42     267  1643.6
   312.7  1635.8  322.641632.809   332.4 1631.24   355.3  1631.2  364.591628.047
   374.9 1622.69   401.5 1618.68   407.6 1618.14   420.7 1618.21   433.8 1620.23
   437.1 1622.55   443.6 1629.96   446.9 1632.01     473 1637.38  481.431641.676
   489.4 1647.65   505.8 1650.94  522.351661.536     653 1726.97   662.8 1732.79
#Mann= 11 ,-1 , 0
       0     .06       0   53.73     .12       0  133.15    .016       0
  172.46     .06       0  178.22     .12       0  322.64    .016       0
  364.59     .12       0   401.5    .045       0   420.7     .12       0
  481.43    .016       0  522.35     .12       0
Bank Sta=401.5,420.7
XS Rating Curve= 0 ,0
Exp/Cntr=0.3,0.1

Type RM Length L Ch R = 1 ,4891    ,436.8,449.1,457.8
XS GIS Cut Line= 2
     2020025.912      219841.404     2020196.603      219313.402
#Sta/Elev= 30
       0 1684.04    2.171683.284   32.571672.707   94.661669.322   125.71665.805
  138.111662.805   153.4 1657.63   163.2  1652.1  187.781651.255   199.1 1647.47
   212.2 1645.81  218.831643.581   261.1 1635.46   280.7 1630.04   293.8 1620.65
   306.8 1607.42   319.9 1596.42   326.4 1594.17     346 1591.62   354.8 1590.73
   365.6 1592.78   375.4 1598.94   388.4 1614.22   401.5  1627.6   404.8 1629.58
   443.9 1639.97  454.011644.722     470 1647.84  484.191656.549   554.9 1691.68
#Mann= 12 ,-1 , 0
       0     .06       0    2.17     .12       0   32.57     .08       0
   94.66     .06       0   125.7     .12       0  138.11    .016       0
  187.78     .08       0  218.83     .12       0     346    .045       0
   365.6     .12       0  454.01    .016       0  484.19     .12       0
Bank Sta=346,365.6
XS Rating Curve= 0 ,0
Exp/Cntr=0.3,0.1

Type RM Length L Ch R = 1 ,4441.9  ,354.6,353.2,349.3
XS GIS Cut Line= 3
       2020336.3       219913.06     2020520.762      219722.088
     2020581.526      219539.797
#Sta/Elev= 30
       0 1657.13   11.231651.004    16.4 1649.33    29.5  1649.6    42.6 1648.24
    45.9 1646.66   56.771637.726    78.7 1626.74   104.9 1615.92   114.7 1610.27
   121.3 1602.54   131.1 1585.26   137.7 1578.86   144.2 1576.52   154.1 1576.25
   163.9 1576.54   180.3 1576.91   186.8  1578.5   203.2 1586.81   226.2  1605.5
   239.3 1610.19     360 1617.83     373 1622.35   382.8 1627.92   392.5 1639.17
     399 1644.21  414.711648.764   428.4  1651.3   441.4 1651.87   457.7 1656.24
#Mann= 6 ,-1 , 0
       0     .12       0   11.23    .016       0   56.77     .12       0
   144.2    .045       0   163.9     .12       0  414.71    .016       0
Bank Sta=144.2,163.9
XS Rating Curve= 0 ,0
Exp/Cntr=0.3,0.1

Type RM Length L Ch R = 1 ,4088.7  ,197.7,196,193.9
XS GIS Cut Line= 3
      2020642.29       220056.29     2020833.262      219808.894
     2020857.134      219670.005
#Sta/Elev= 30
       0 1683.37    16.3 1675.02    29.3  1665.7    42.3 1662.72    52.1 1654.86
   57.841645.638    65.1 1633.07    68.4 1631.37    91.2 1630.92    94.4    1630
   98.561625.231   104.2 1615.97   113.9 1607.04     153 1576.08   162.8 1569.58
   175.8 1564.59   212.8 1560.47   218.1 1560.13   227.8 1560.61   234.4 1563.39
   247.4 1576.61   253.9 1581.06   276.7 1580.04   328.9 1597.66     365 1602.12
   374.8 1605.82     401 1620.81   417.4 1625.34   446.9  1629.7   453.5  1632.6
#Mann= 5 ,-1 , 0
       0     .12       0   57.84    .016       0   98.56     .12       0
   212.8    .045       0   227.8     .12       0
Bank Sta=212.8,227.8
XS Rating Curve= 0 ,0
Exp/Cntr=0.3,0.1

Type RM Length L Ch R = 1 ,3892.8  ,306.7,300.5,293.2
XS GIS Cut Line= 3
     2020841.943      220136.585     2021013.384      219871.828
     2021022.064      219739.449
#Sta/Elev= 30
       0 1652.75    1.461650.638     3.2 1648.12     6.5  1641.4      13  1626.9
    16.3 1623.03      26  1615.6   36.651614.763   65.591613.936    84.5 1613.69
      91 1610.49    97.6 1605.11   117.1 1583.29   126.8 1566.38   130.1 1562.36
   139.8  1557.1   146.3 1555.44   156.1 1554.58   172.3 1555.47   204.9 1559.34
   214.6 1558.53   224.4 1555.53   227.6 1555.82   250.4 1562.74   286.2 1576.46
   331.6 1583.18   402.8 1605.32     419 1613.39   431.9 1622.76   448.1 1630.08
#Mann= 6 ,-1 , 0
       0     .12       0    1.46     .06       0   36.65    .016       0
   65.59     .12       0   146.3    .045       0   172.3     .12       0
#XS Ineff= 2 , 0
                          217.07         1564.14
Permanent Ineff=
       F       F
Bank Sta=146.3,172.3
XS Rating Curve= 0 ,0
Exp/Cntr=0.3,0.1

Type RM Length L Ch R = 1 ,3592.2  ,143.6,127.2,110.6
XS GIS Cut Line= 4
      2021269.46      220327.557     2021168.766       220212.54
     2021215.641      220051.081     2021172.238      219861.845
#Sta/Elev= 30
       0 1657.67    45.5 1642.05    58.5 1635.99      65 1631.15    81.3 1604.47
    84.6 1601.04    94.3 1594.36  119.591593.792   133.4 1594.84  161.561593.878
     169 1594.62   175.5 1593.05   198.1  1577.2   211.1 1570.34   230.5 1553.96
   240.2  1549.5   261.8 1543.56   269.3 1542.95   276.8 1543.09   285.4 1544.43
   291.9 1550.99   301.6 1552.88   366.3 1548.47   372.8 1549.71   385.7 1556.65
   398.6 1559.36   453.7 1558.58   492.5 1560.99     499 1562.71   515.1 1572.74
#Mann= 5 ,-1 , 0
       0     .12       0  119.59    .016       0  161.56     .12       0
   261.8    .045       0   276.8     .12       0
#XS Ineff= 2 , 0
                          301.87         1562.71
Permanent Ineff=
       F       F
Bank Sta=261.8,276.8
XS Rating Curve= 0 ,0
Exp/Cntr=0.3,0.1

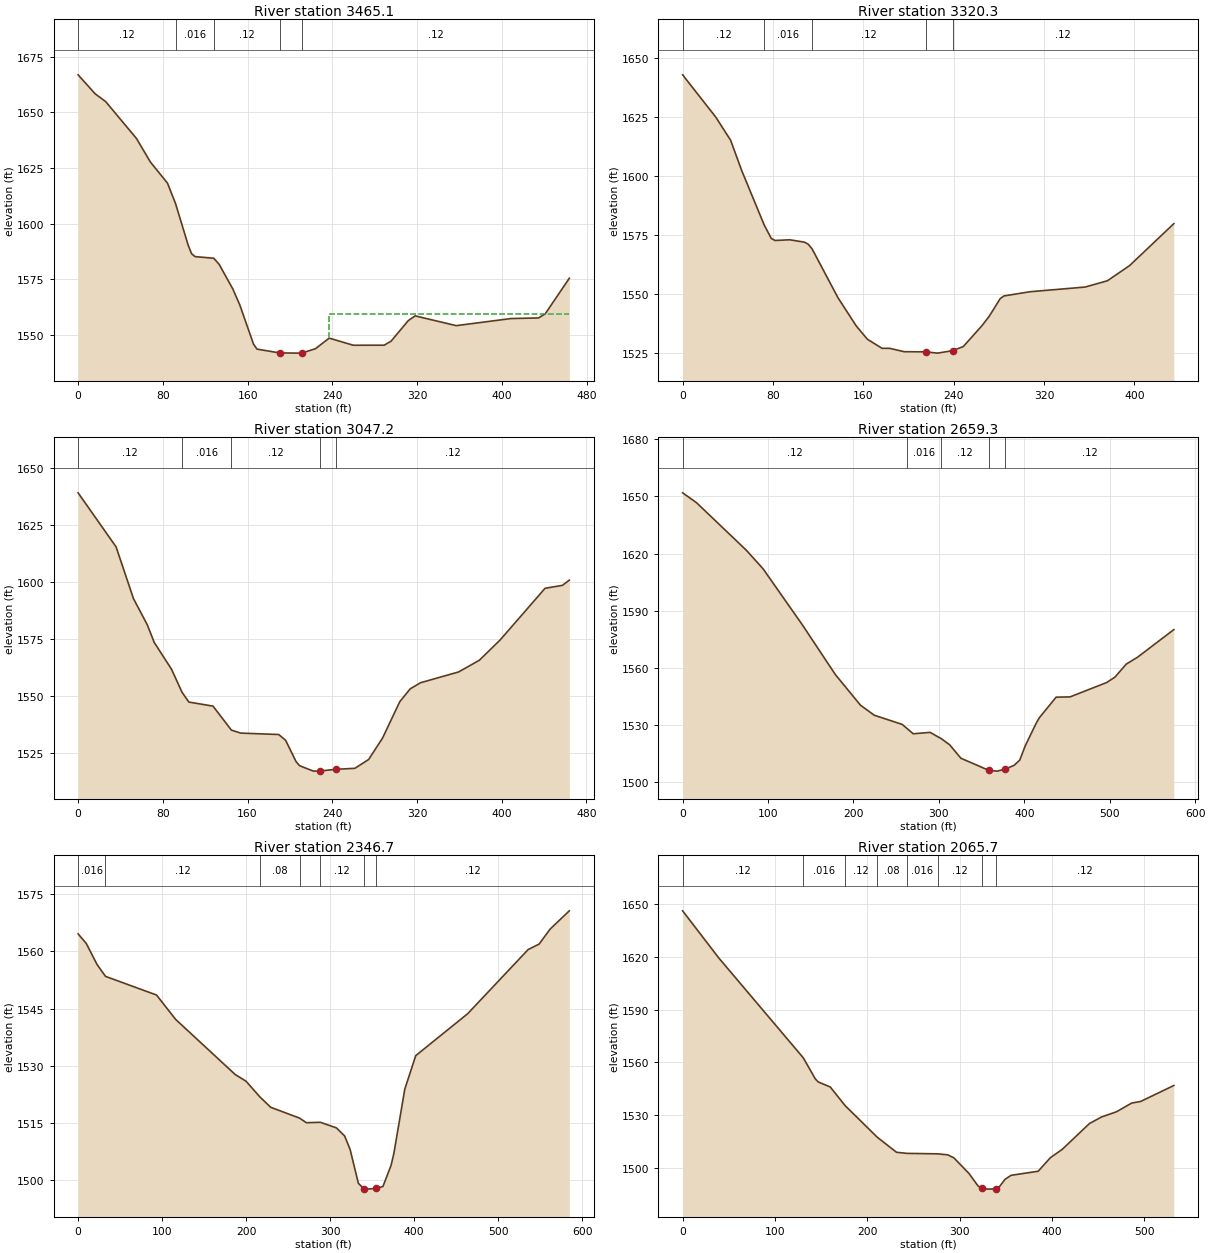
Type RM Length L Ch R = 1 ,3465.1  ,147.7,144.8,139.9
XS GIS Cut Line= 3
     2021410.085      220266.359     2021276.405      219992.053
     2021250.363      219835.803
#Sta/Elev= 30
       0 1666.83    16.2 1658.26      26 1654.83    55.2 1638.19    68.2  1627.7
    84.4 1618.16   91.991608.993   103.9 1590.33   107.1 1586.51   110.4  1585.2
  128.011584.471   133.1 1581.77   146.1  1570.6   152.6 1563.51   165.6 1545.87
   168.8 1543.67   190.4 1541.94     211 1541.86     224 1543.84     237  1548.6
   259.7  1545.4   288.9 1545.42   295.4 1547.23   311.6 1556.45   318.1 1558.59
   356.9  1554.2   408.6 1557.39   434.5 1557.66   440.9 1559.51   463.6 1575.48
#Mann= 5 ,-1 , 0
       0     .12       0   91.99    .016       0  128.01     .12       0
   190.4    .045       0     211     .12       0
#XS Ineff= 2 , 0
                          236.86          1559.5
Permanent Ineff=
       F       F
Bank Sta=190.4,211
XS Rating Curve= 0 ,0
Exp/Cntr=0.3,0.1

Type RM Length L Ch R = 1 ,3320.3  ,274.8,273.1,269.9
XS GIS Cut Line= 2
     2021547.238      220162.626     2021291.161      219811.064
#Sta/Elev= 30
       0 1642.84    29.4 1624.89    42.5 1615.12    52.3  1602.3   72.231579.225
    78.5 1573.52    81.8 1572.66    94.8 1572.95   107.9 1571.95   111.2 1571.07
  114.621569.106   137.4 1548.52   153.7 1536.46   163.5 1530.85   176.6 1526.95
   183.1 1526.98   196.2 1525.54   215.8 1525.46   225.6 1524.93   239.1 1525.98
   248.5 1527.72   264.9 1536.49   271.4 1540.51   281.2 1548.04   284.5 1549.16
   307.4 1550.93   356.4 1552.93   376.1 1555.59   395.7    1562   434.9 1579.78
#Mann= 5 ,-1 , 0
       0     .12       0   72.23    .016       0  114.62     .12       0
   215.8    .045       0   239.1     .12       0
Bank Sta=215.8,239.1
XS Rating Curve= 0 ,0
Exp/Cntr=0.3,0.1

Type RM Length L Ch R = 1 ,3047.2  ,384.3,387.9,389.4
XS GIS Cut Line= 2
     2021775.102      219978.165     2021462.602      219635.283
#Sta/Elev= 30
       0 1639.21    35.9 1615.43    52.3  1592.7    65.3 1581.25    71.9 1573.44
    88.2 1561.69   98.131551.563   104.6 1547.23   127.4 1545.45  144.781534.908
   153.6 1533.59   189.5 1532.96     196 1530.42   205.8  1521.1   209.1 1519.28
   222.2 1516.87   228.7 1516.94   243.7 1517.67   261.4 1518.11   274.4 1521.98
   287.5 1531.38   303.8 1547.39   313.6 1553.02   323.4 1555.73   359.4 1560.47
     379 1565.63   398.6 1574.54     441 1597.24   457.4 1598.54   463.9 1600.82
#Mann= 5 ,-1 , 0
       0     .12       0   98.13    .016       0  144.78     .12       0
   228.7    .045       0   243.7     .12       0
Bank Sta=228.7,243.7
XS Rating Curve= 0 ,0
Exp/Cntr=0.3,0.1

Type RM Length L Ch R = 1 ,2659.3  ,297.5,312.6,327.5
XS GIS Cut Line= 3
     2021931.352      219858.807     2021909.651       219596.22
     2021723.019      219346.654
#Sta/Elev= 30
       0 1651.82    16.3 1646.64    74.8 1621.62    94.3 1611.91   139.9 1582.78
   178.9 1556.48   208.2 1540.48   224.4 1535.19     257 1530.41  262.911528.169
     270 1525.47   289.7 1526.21  302.851522.907   312.7 1519.69   325.8 1512.65
   358.6 1506.28   368.4 1505.89   377.6 1506.94   388.1 1508.93   394.7 1511.67
   401.3 1519.32   414.4 1531.39   417.7 1533.92   437.3 1544.67   453.7 1544.83
   496.4 1552.33   506.2 1555.19   519.4    1562   532.5 1565.58   575.1  1580.1
#Mann= 5 ,-1 , 0
       0     .12       0  262.91    .016       0  302.85     .12       0
   358.6    .045       0   377.6     .12       0
Bank Sta=358.6,377.6
XS Rating Curve= 0 ,0
Exp/Cntr=0.3,0.1

Type RM Length L Ch R = 1 ,2346.7  ,291.1,281,270.7
XS GIS Cut Line= 4
     2022220.849      219780.248     2022125.363      219630.942
     2022134.043      219344.484     2022069.807      219242.053
#Sta/Elev= 30
       0 1564.57     9.7 1562.07    22.6 1556.53    32.61553.435    93.4 1548.54
     116 1542.18     187 1527.71     200 1525.94     2161521.931   229.3 1519.11
  263.591516.289   271.7 1515.08  288.441515.183   307.5 1513.72   317.3 1511.59
   323.8 1508.07   333.6 1499.21   340.1 1497.77   343.3 1497.67   355.1 1497.86
   362.9 1498.37   372.6 1503.94   375.9 1507.06   388.9 1523.89   401.9 1532.65
   463.8 1543.66   535.7 1560.46   548.8  1561.9   561.8 1565.81   584.7 1570.61
#Mann= 7 ,-1 , 0
       0    .016       0    32.6     .12       0     216     .08       0
  263.59    .016       0  288.44     .12       0   340.1    .045       0
   355.1     .12       0
Bank Sta=340.1,355.1
XS Rating Curve= 0 ,0
Exp/Cntr=0.3,0.1

Type RM Length L Ch R = 1 ,2065.7  ,316.6,313.5,310
XS GIS Cut Line= 2
     2022541.517      219736.936     2022323.793      219251.511
#Sta/Elev= 30
       0 1646.15    39.2 1619.35  130.661562.626   143.6 1550.73   146.9 1548.89
   159.9 1546.05  175.861535.536  210.761517.514   231.7 1508.93  243.141508.315
  276.311508.048   287.2 1507.48   293.8 1505.77   310.1 1496.93   319.9 1489.84
     324 1488.53   329.6    1488     339 1488.14   342.7 1489.09   349.2 1493.58
   355.8 1495.86   385.1 1498.16   398.2 1505.81   411.2 1510.63   440.6 1525.27
   453.7    1529     470 1531.98   486.3  1536.9   496.1 1537.83     532 1546.89
#Mann= 8 ,-1 , 0
       0     .12       0  130.66    .016       0  175.86     .12       0
  210.76     .08       0  243.14    .016       0  276.31     .12       0
     324    .045       0     339     .12       0
Bank Sta=324,339
XS Rating Curve= 0 ,0
Exp/Cntr=0.3,0.1

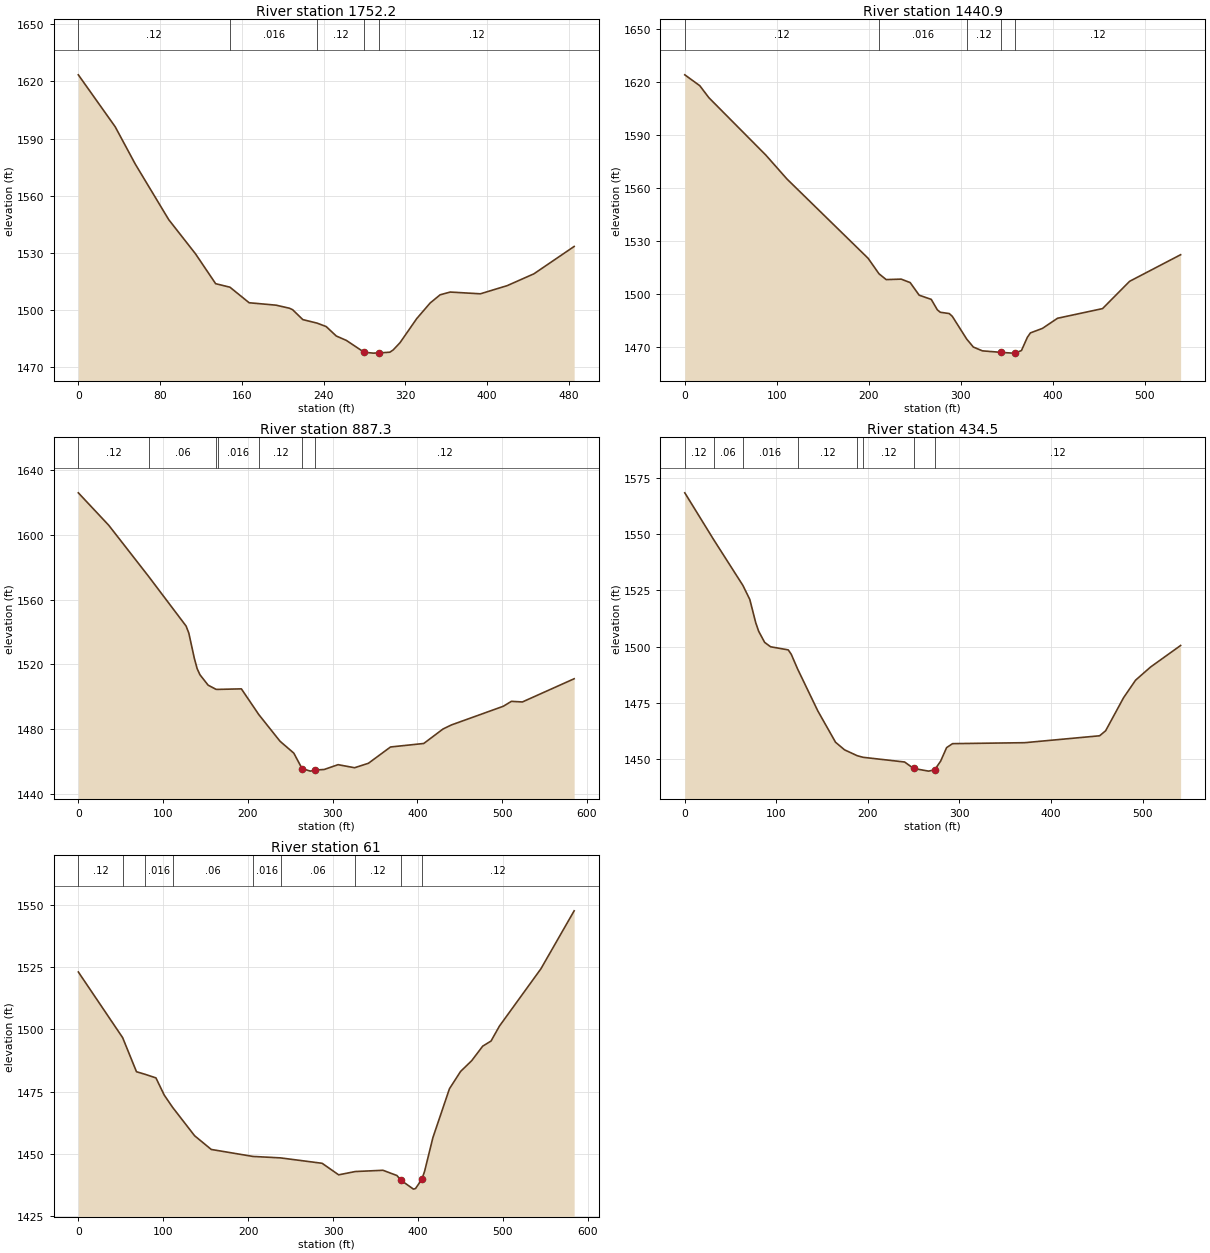
Type RM Length L Ch R = 1 ,1752.2  ,304.5,311.3,316.9
XS GIS Cut Line= 2
     2022835.607      219529.448     2022574.407      219120.458
#Sta/Elev= 30
       0  1623.5    36.1 1596.16    55.7 1576.57    88.5  1547.3   114.8 1529.25
   134.4 1513.62  148.391511.776   167.2 1503.59   193.5 1502.32   206.6 1500.72
   209.8 1499.91   219.7 1494.73  233.84 1492.85   242.6 1491.06   252.5 1486.09
   262.3 1483.79   279.7 1477.56   288.6 1477.09   294.7  1477.2   304.9 1477.58
   308.2 1478.78   314.8 1482.54   331.2 1495.24   344.3 1503.43   354.1 1507.77
     364 1509.22   393.5  1508.3   419.7 1512.58   445.9 1518.81   485.3 1533.21
#Mann= 5 ,-1 , 0
       0     .12       0  148.39    .016       0  233.84     .12       0
   279.7    .045       0   294.7     .12       0
Bank Sta=279.7,294.7
XS Rating Curve= 0 ,0
Exp/Cntr=0.3,0.1

Type RM Length L Ch R = 1 ,1440.9  ,528.9,553.6,576.4
XS GIS Cut Line= 3
     2023027.021      219436.915     2022895.568      219019.138
      2022808.34      218967.765
#Sta/Elev= 30
       0 1624.05    16.3  1617.9    26.2 1611.11    88.2 1578.62   111.1 1565.14
   199.4 1520.27  211.13 1511.58     219 1508.25   235.3 1508.52   245.1 1506.56
   254.9 1499.43     268 1497.07   274.6 1491.19   277.8 1489.79   287.6 1489.04
   290.9 1487.49  306.581474.606   313.8 1470.11   323.6 1467.96   344.4 1467.08
   356.3 1466.67   359.4 1466.74   366.1 1468.13   372.6 1475.69   375.9 1478.12
   388.9 1480.65   405.3 1486.38   454.3 1491.85   483.7 1507.27   539.2 1522.32
#Mann= 5 ,-1 , 0
       0     .12       0  211.13    .016       0  306.58     .12       0
   344.4    .045       0   359.4     .12       0
Bank Sta=344.4,359.4
XS Rating Curve= 0 ,0
Exp/Cntr=0.3,0.1

Type RM Length L Ch R = 1 ,887.3   ,459.6,452.8,443.6
XS GIS Cut Line= 3
     2023183.523      219429.119     2023489.512      219099.258
     2023502.533       218964.71
#Sta/Elev= 30
       0 1626.04    35.9 1605.97   82.971574.327   127.2 1543.63   130.4 1539.28
   136.9 1523.69   140.2 1517.35   143.5 1513.55   153.2 1507.08  162.56 1504.52
  164.74 1504.48   192.4 1504.82  213.03 1488.86     238 1472.43   254.3 1465.06
     264 1455.51   273.9 1453.94     279 1454.57   290.2 1454.97   306.5 1457.93
     326 1456.04   342.3 1458.79   368.4 1468.87   407.6 1471.03   430.4 1480.01
   440.2 1482.49   501.4 1494.03   511.1  1497.1     524 1496.71   585.1 1511.06
#Mann= 7 ,-1 , 0
       0     .12       0   82.97     .06       0  162.56     .12       0
  164.74    .016       0  213.03     .12       0     264    .045       0
     279     .12       0
Bank Sta=264,279
XS Rating Curve= 0 ,0
Exp/Cntr=0.3,0.1

Type RM Length L Ch R = 1 ,434.5   ,362.6,373.5,383.1
XS GIS Cut Line= 3
     2023531.613       219658.72     2023670.502      219570.178
     2023812.863       219221.22
#Sta/Elev= 30
       0 1568.36   31.46 1547.63   63.461527.263      71 1521.02    77.5 1510.67
    80.7  1506.9    87.2 1501.98    93.7 1500.02     113 1498.63   116.3 1496.68
  123.141490.229   145.3 1471.54   164.7 1457.61   174.5 1454.26  188.441451.641
  194.841450.942   240.1 1448.86   249.9    1446   266.3 1444.81   272.9 1445.36
   279.4  1449.2     286 1455.26   292.5 1457.01   371.2 1457.43   453.1  1460.5
   459.7 1462.74   479.3 1477.42   492.4 1485.19   508.8 1491.04   541.6 1500.59
#Mann= 8 ,-1 , 0
       0     .12       0   31.46     .06       0   63.46    .016       0
  123.14     .12       0  188.44     .06       0  194.84     .12       0
   249.9    .045       0   272.9     .12       0
Bank Sta=249.9,272.9
XS Rating Curve= 0 ,0
Exp/Cntr=0.3,0.1

Type RM Length L Ch R = 1 ,61      ,58,61,64
XS GIS Cut Line= 2
     2023741.682      219903.078      2024177.88      219514.623
#Sta/Elev= 30
       0 1523.03    52.2 1496.65    68.5 1482.95    78.3 1481.95    91.4 1480.48
   101.2 1473.57     111 1468.67     137 1457.22   156.6 1451.72   205.6 1448.92
   238.2 1448.33   287.2 1446.16   306.7 1441.52   326.3 1442.85   358.9 1443.35
   375.3 1441.25   380.4 1439.25   394.8 1435.78  397.25 1436.02   404.6  1439.7
   407.9 1442.92   417.7 1456.48   437.2 1476.12   450.3 1483.06   463.4 1487.39
   476.4 1493.24   486.2 1495.29     496 1501.25   544.9 1524.29   584.1  1547.6
#Mann= 9 ,-1 , 0
       0     .12       0    52.2     .06       0    78.3    .016       0
     111     .06       0   205.6    .016       0   238.2     .06       0
   326.3     .12       0   380.4    .045       0   404.6     .12       0
Bank Sta=380.4,404.6
XS Rating Curve= 0 ,0
Exp/Cntr=0.3,0.1

Chan Stop Cuts=-1
Use User Specified Reach Order=0
Composite Channel Slope=5